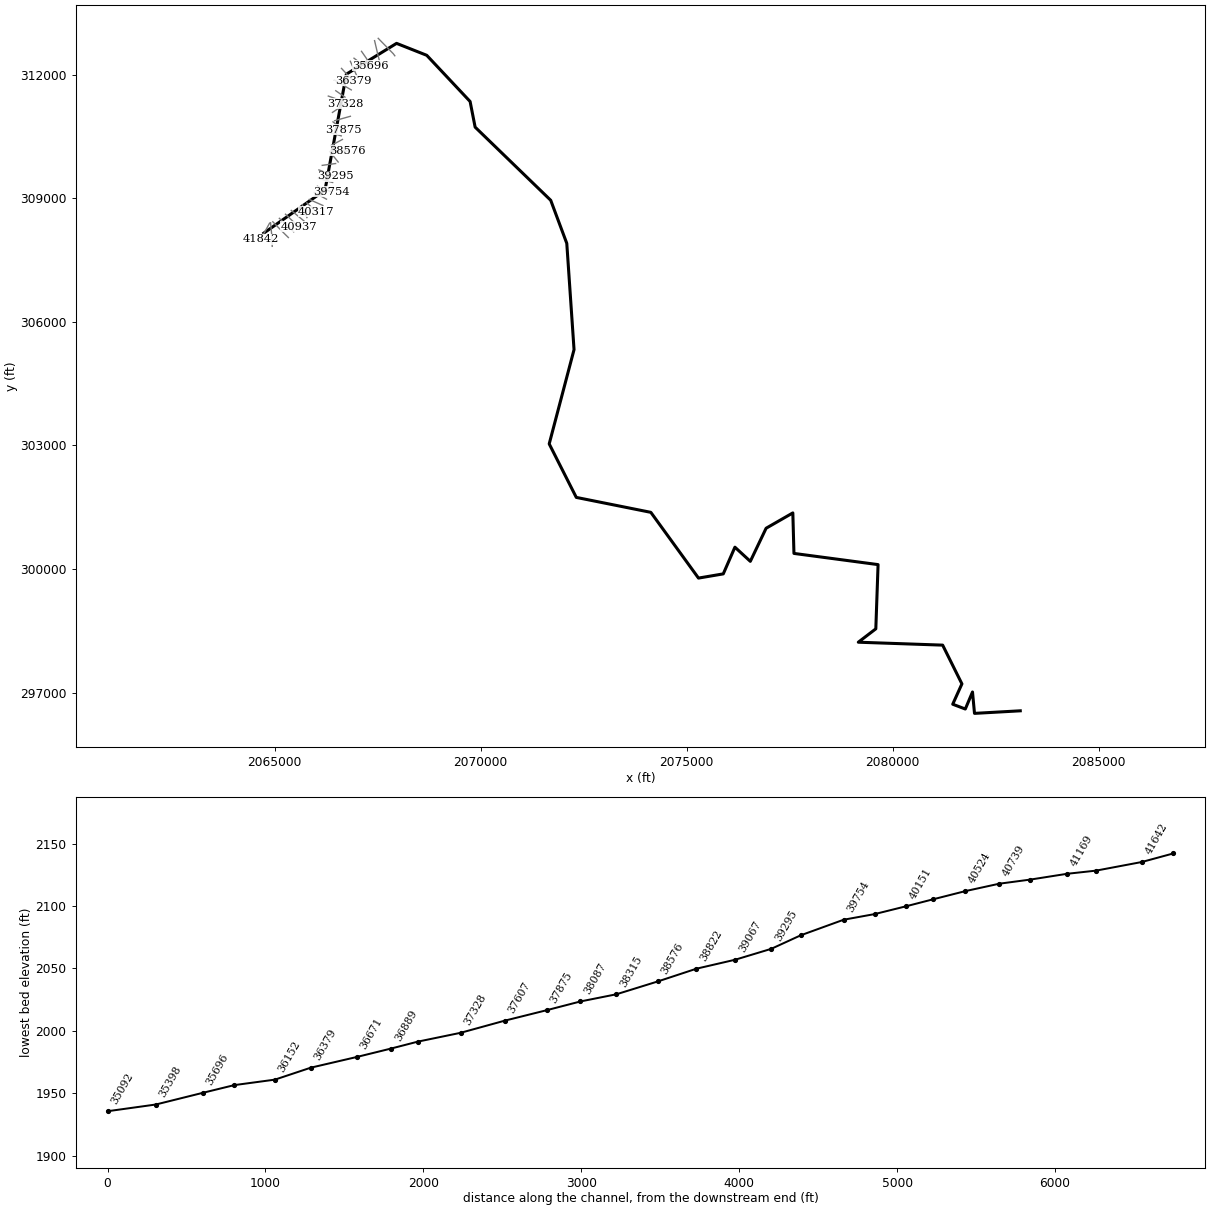
--- KTCHNCK.prj (project) ---

Proj Title=KTCHNCK
Current Plan=p01
Default Exp/Contr=0.3,0.1
English Units
Geom File=g01
Flow File=f01
Plan File=p01
Y Axis Title=Elevation
X Axis Title(PF)=Main Channel Distance
X Axis Title(XS)=Station
BEGIN DESCRIPTION:
Stream Name- Kitchen Creek
Flood Zone: Zone A
Greenbrier County, WV
County-Wide Study
WVDHSEM-2018-3, Flood Risk Project
HEC-RAS Version: 5.0.7
General Notes:
For the Hydrology Regression was used.
END DESCRIPTION:
DSS File=dss
DSS Export Rating Curves= 0
DSS Export Rating Curve Sorted= 0
DSS Export Volume Flow Curves= 0
DXF Filename=..\J2.
DXF OffsetX= 0
DXF OffsetY= 0
DXF ScaleX= 1
DXF ScaleY= 10

--- KTCHNCK.p01 (plan) ---

Plan Title=Floodplain
Program Version=5.07
Short Identifier=Floodplain
Geom File=g01
Flow File=f01
Subcritical Flow
K Sum by GR= 0
Std Step Tol= 0.01
Critical Tol= 0.01
Num of Std Step Trials= 20
Max Error Tol= 0.3
Flow Tol Ratio= 0.001
Split Flow NTrial= 30
Split Flow Tol= 0.02
Split Flow Ratio= 0.02
Log Output Level= 0
Friction Slope Method= 1
Unsteady Friction Slope Method= 2
Unsteady Bridges Friction Slope Method= 1
Parabolic Critical Depth
Global Vel Dist= 0 , 0 , 0
Global Log Level= 0
CheckData=True
Encroach Param=-1 ,0,0, 0
Computation Interval=1MIN
Output Interval=1HOUR
Instantaneous Interval=1HOUR
Mapping Interval=1HOUR
Computation Time Step Use Courant=        0
Computation Time Step Use Time Series=    0
Computation Time Step Count To Double=0
Computation Time Step Max Doubling=0
Computation Time Step Max Halving=0
Computation Time Step Residence Courant=0
Run HTab= 0
Run UNet= 0
Run Sediment= 0
Run PostProcess= 0
Run WQNet= 0
Run RASMapper= 0
UNET Theta= 1
UNET Theta Warmup= 1
UNET ZTol= 0.02
UNET ZSATol= 0.02
UNET MxIter= 20
UNET Max Iter WO Improvement= 0
UNET MaxInSteps= 0
UNET DtIC= 0
UNET DtMin= 0
UNET MaxCRTS= 20
UNET WFStab= 2
UNET SFStab= 1
UNET WFX= 1
UNET SFX= 1
UNET 1D Methodology=Finite Difference
UNET DSS MLevel= 4
UNET Pardiso=0
UNET DZMax Abort= 100
UNET Use Existing IB Tables=-1
UNET Froude Reduction=False
UNET Froude Limit= 0.8
UNET Froude Power= 4
UNET D1 Cores= 0
UNET D2 Coriolis=0
UNET D2 Cores= 0
UNET D2 Theta= 1
UNET D2 Theta Warmup= 1
UNET D2 Z Tol= 0.01
UNET D2 Volume Tol= 0.01
UNET D2 Max Iterations= 20
UNET D2 Equation= 0
UNET D2 RampUpFraction=0.1
UNET D2 TimeSlices= 1
UNET D2 BCVolumeCheck=0
UNET D1D2 MaxIter= 0
UNET D1D2 ZTol=0.01
UNET D1D2 QTol=0.1
UNET D1D2 MinQTol=1
DSS File=dss
Write IC File= 0
Write IC File at Fixed DateTime=0
Write IC File at Sim End=0
Echo Input=False
Echo Parameters=False
Echo Output=False
Write Detailed= 0
HDF Write Warmup=0
HDF Write Time Slices=0
HDF Flush=0
HDF Face Node Velocities=0
HDF Compression= 1
HDF Chunk Size= 1
HDF Spatial Parts= 1
HDF Use Max Rows=0
HDF Fixed Rows= 1
Calibration Method= 0
Calibration Iterations= 20
Calibration Max Change=0.05
Calibration Tolerance=0.2
Calibration Maximum=1.5
Calibration Minimum=0.5
Calibration Optimization Method= 1
WQ AD Non Conservative
WQ ULTIMATE=-1
WQ Max Comp Step=1HOUR
WQ Output Interval=15MIN
WQ Output Selected Increments= 0
WQ Output face flow=0
WQ Output face velocity=0
WQ Output face area=0
WQ Output face dispersion=0
WQ Output cell volume=0
WQ Output cell surface area=0
WQ Output cell continuity=0
WQ Output cumulative cell continuity=0
WQ Output face conc=0
WQ Output face dconc_dx=0
WQ Output face courant=0
WQ Output face peclet=0
WQ Output face adv mass=0
WQ Output face disp mass=0
WQ Output cell mass=0
WQ Output cell source sink temp=0
WQ Output nsm pathways=0
WQ Output nsm derived pathways=0
WQ Output MaxMinRange=-1
WQ Daily Max Min Mean=-1
WQ Daily Range=0
WQ Daily Time=0
WQ Create Restart=0
WQ Fixed Restart=0
WQ System Summary=0
WQ Write To DSS=0
WQ Use Fixed Temperature=0
Sorting and Armoring Iterations= 10
XS Update Threshold= 0.02
Bed Roughness Predictor= 0
Hydraulics Update Threshold= 0.02
Energy Slope Method= 1
Volume Change Method= 1
Sediment Retention Method= 0
XS Weighting Method= 0
Number of US Weighted Cross Sections= 1
Number of DS Weighted Cross Sections= 1
Upstream XS Weight=0
Main XS Weight=1
Downstream XS Weight=0
Number of DS XS's Weighted with US Boundary= 1
Upstream Boundary Weight= 1
Weight of XSs Associated with US Boundary= 0
Number of US XS's Weighted with DS Boundary= 1
Downstream Boundary Weight= 0.5
Weight of XSs Associated with DS Boundary= 0.5
Percentile Method= 0
Sediment Output Level= 3
Mass or Volume Output= 0
Output Increment Type= 1
Profile and TS Output Increment= 1
XS Output Flag= 0
XS Output Increment= 10
Write Gradation File= 0
Read Gradation Hotstart= 0
Write HDF5 File= 1
Write Binary Output= 1
Write DSS Sediment File= 0
SV Curve= 0
Specific Gage Flag= 0

--- KTCHNCK.f01 (steady flow) ---

Flow Title=Flow
Program Version=5.07
Number of Profiles= 6
Profile Names=f1p,f10p,f4p,f2p,f02p,f1pplus
River Rch & RM=KTCHNCK,Main            ,41842
     743     397     525     631    1030    1100
River Rch & RM=KTCHNCK,Main            ,37328
     832     446     589     707    1150    1230
River Rch & RM=KTCHNCK,Main            ,35092
     926     499     657     788    1280    1370
River Rch & RM=KTCHNCK,Main            ,33009
    1030     557     732     876    1420    1520
River Rch & RM=KTCHNCK,Main            ,28691
    1150     622     817     977    1580    1700
River Rch & RM=KTCHNCK,Main            ,21556
    1810    1000    1300    1550    2480    2680
River Rch & RM=KTCHNCK,Main            ,16488
    2900    1630    2110    2490    3930    4290
River Rch & RM=KTCHNCK,Main            ,10721
    3870    2200    2830    3340    5220    5730
Boundary for River Rch & Prof#=KTCHNCK,Main            , 1
Up Type= 0
Dn Type= 3
Dn Slope=0.0006
Boundary for River Rch & Prof#=KTCHNCK,Main            , 2
Up Type= 0
Dn Type= 3
Dn Slope=0.0006
Boundary for River Rch & Prof#=KTCHNCK,Main            , 3
Up Type= 0
Dn Type= 3
Dn Slope=0.0006
Boundary for River Rch & Prof#=KTCHNCK,Main            , 4
Up Type= 0
Dn Type= 3
Dn Slope=0.0006
Boundary for River Rch & Prof#=KTCHNCK,Main            , 5
Up Type= 0
Dn Type= 3
Dn Slope=0.0006
Boundary for River Rch & Prof#=KTCHNCK,Main            , 6
Up Type= 0
Dn Type= 3
Dn Slope=0.0006
DSS Import GetInterval= 0
DSS Import GetPeak= 0
DSS Import FillOption= 0

--- KTCHNCK.g01 (geometry) ---

Geom Title=Geometry
Program Version=5.07

River Reach=KTCHNCK         ,Main
Reach XY= 30
2064741.66449693308152.7780552952066225.25995493309194.494147718
 2066743.1870687312008.2221160382067961.78896219312756.435842708
 2068694.4269326312466.4649659542069746.74635029311345.823834538
2069869.04203743310723.1190432162071703.31888068308947.919837713
2072093.23050243 307902.551193552072269.33185628 305323.88705954
2071666.53811437303035.9579083772072323.81895202301737.162933797
2074133.13193443301374.5468611272075289.56006777299778.907007799
2075891.14711919299881.0236014572076173.78598961300528.940284625
2076547.39711902300185.1899878832076930.73066995300988.662462294
2077579.34157744301360.884486884 2077606.4251847300377.551151708
2079648.09170502300106.0234795512079593.23059428298547.689982042
2079168.23046002298222.6899758732081215.45274353 298151.85678421
2081682.81401351297211.5791372062081459.89713651296717.829140455
2081765.45295587296601.1623790412081939.75838152297015.051315039
2081988.36950478296495.6068158752083099.10612845296557.853082463

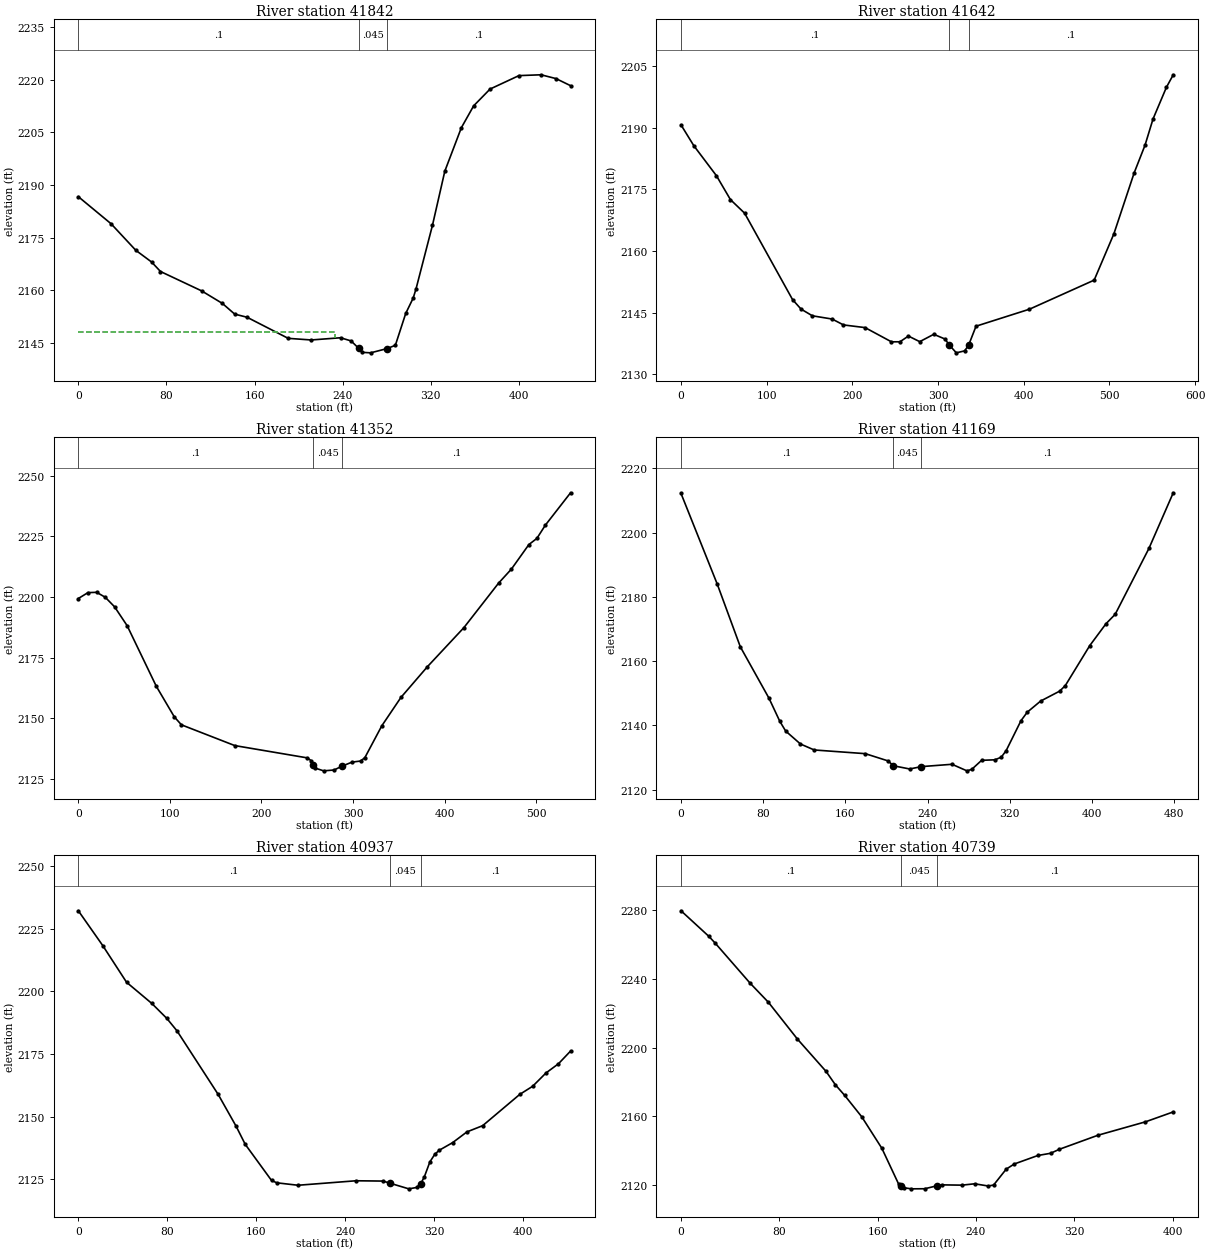
Type RM Length L Ch R = 1 ,41842   ,192.3,200.7,205.4
XS GIS Cut Line= 2
 2064879.1907967308391.6450316312064664.34706628 307999.71799396
#Sta/Elev= 30
       0 2186.67    29.7 2178.96    52.2 2171.38    66.5 2168.05    74.6 2165.34
     112 2159.81   130.8 2156.24     142 2153.19   153.2  2152.3   190.6 2146.28
   211.5 2145.82   238.1 2146.45   247.7 2145.55  254.472143.472     258 2142.29
   265.4 2142.15  280.572143.381   287.9 2144.31   297.3 2153.38   304.1 2157.78
   306.6 2160.31   321.6 2178.53   332.8 2193.94   347.8 2206.32     359 2212.58
   373.9 2217.36   400.1 2221.19   420.2 2221.43   433.8 2220.34     447 2218.32
#Mann= 3 ,-1 , 0
       0      .1       0  254.47    .045       0  280.57      .1       0
#XS Ineff= 2 , 0
          232.69 2148.21
Permanent Ineff=
       F       F
Bank Sta=254.47,280.57
XS Rating Curve= 0 ,0
Exp/Cntr=0.3,0.1

Type RM Length L Ch R = 1 ,41642   ,279,289.3,296.6
XS GIS Cut Line= 3
2064903.93057659308403.3638402072064931.27435395308118.207586378
2064944.29499719307830.447007045
#Sta/Elev= 30
       0  2190.7    14.9 2185.65    41.3 2178.35    57.7 2172.52    74.2 2169.23
   130.2 2148.19   140.1 2145.89   153.3 2144.26   176.4 2143.47   189.6 2142.04
   214.8 2141.39   245.6 2137.93   255.5 2137.94   265.4 2139.33   278.6 2137.97
     295 2139.76   308.2  2138.6  312.652137.263   321.3 2135.25     331 2135.73
  335.632137.096   344.3 2141.73   406.7 2145.87   482.2 2152.94   505.2  2164.2
   528.9 2179.05   541.5 2185.74   550.9 2192.15   566.6 2199.89   574.5  2202.9
#Mann= 3 ,-1 , 0
       0      .1       0  312.65    .045       0  335.63      .1       0
Bank Sta=312.65,335.63
XS Rating Curve= 0 ,0
Exp/Cntr=0.3,0.1

Type RM Length L Ch R = 1 ,41352   ,182.1,183.1,183.5
XS GIS Cut Line= 3
2064958.61813128308426.8014573752065163.76831153 308214.97182855
2065336.22236294308043.988902792
#Sta/Elev= 30
       0 2199.39    10.5 2201.81      20 2201.94    29.4  2199.9    39.6 2195.96
    53.3 2188.19    85.2 2163.18   104.8 2150.62   112.6 2147.32   170.9 2138.76
   250.3 2133.68   254.2 2132.55  256.862130.633   258.8 2129.48   267.9 2128.35
   279.3 2128.69  288.332130.336   299.1 2131.95   308.3 2132.39     313 2133.79
   331.5 2146.91   352.4 2158.61   381.3 2171.27   421.2 2187.39   459.1 2205.74
   473.1 2211.52   492.2 2221.64   500.9 2224.16   510.2 2229.64   537.7 2242.97
#Mann= 3 ,-1 , 0
       0      .1       0  256.86    .045       0  288.33      .1       0
Bank Sta=256.86,288.33
XS Rating Curve= 0 ,0
Exp/Cntr=0.3,0.1

Type RM Length L Ch R = 1 ,41169   ,228.1,232.4,230.5
XS GIS Cut Line= 2
2065117.47214428308510.1346240492065466.43043587308182.009624124
#Sta/Elev= 30
       0 2212.19    35.2 2184.01    57.7 2164.44    85.6 2148.43    96.1 2141.26
   101.8 2138.22   116.2 2134.18   129.6 2132.32   179.3 2131.17   201.5 2128.91
  206.692127.397   222.5  2126.4  233.932127.135   263.7 2127.86   278.2 2125.82
   282.9 2126.28   292.5 2129.09   305.4 2129.26   311.6 2130.06   316.4 2132.12
   330.8 2141.42   336.9 2144.08   349.9 2147.54   368.4 2150.63   373.9 2152.34
   397.8 2164.84   413.5 2171.61   422.5 2174.57   455.3 2195.06     479 2212.41
#Mann= 3 ,-1 , 0
       0      .1       0  206.69    .045       0  233.93      .1       0
Bank Sta=206.69,233.93
XS Rating Curve= 0 ,0
Exp/Cntr=0.3,0.1

Type RM Length L Ch R = 1 ,40937   ,192.9,197.2,195
XS GIS Cut Line= 2
2065265.90983951308610.3949222122065586.22219104308304.405376717
#Sta/Elev= 30
       0 2232.16      22 2218.25    43.4 2203.63    66.1 2195.19    79.7 2189.18
    88.8 2184.23   125.8 2158.91     142 2146.17   150.2 2138.95   173.9 2124.52
   178.7 2123.59   197.7 2122.62   249.9 2124.41   274.3 2124.29  280.122123.483
   297.4 2121.19   304.4 2121.73  308.212123.286   311.4 2125.97   316.4 2131.95
   320.7 2134.91   324.7 2136.56   336.9 2139.64   349.7 2143.91   363.9  2146.4
   397.3 2158.89   408.9 2162.13   420.9 2167.44   432.1  2171.1     443 2176.18
#Mann= 3 ,-1 , 0
       0      .1       0  280.12    .045       0  308.21      .1       0
Bank Sta=280.12,308.21
XS Rating Curve= 0 ,0
Exp/Cntr=0.3,0.1

Type RM Length L Ch R = 1 ,40739   ,220.3,215.2,207.1
XS GIS Cut Line= 2
2065406.53455827 308701.541065382065715.12842926308446.332586288
#Sta/Elev= 30
       0 2279.66    22.7 2264.74    27.8 2260.84    56.2 2237.54    71.1 2226.42
    94.7 2205.02     118 2186.21   125.6  2178.4   133.1  2172.3   147.1 2159.74
   163.4 2141.47   177.1 2120.58  179.062119.423   181.8 2118.46   187.4 2117.88
   198.3 2117.93  208.372119.685   212.3 2120.19   228.6 2120.03   238.9 2120.81
   249.9 2119.54   254.3 2120.07   264.6 2129.36   271.2 2132.35   290.4 2137.29
   300.7 2138.57   307.9 2140.91   339.3 2149.08   377.9 2156.87   400.5 2162.64
#Mann= 3 , 0 , 0
       0      .1       0  179.06    .045       0  208.37      .1       0
Bank Sta=179.06,208.37
XS Rating Curve= 0 ,0
Exp/Cntr=0.3,0.1

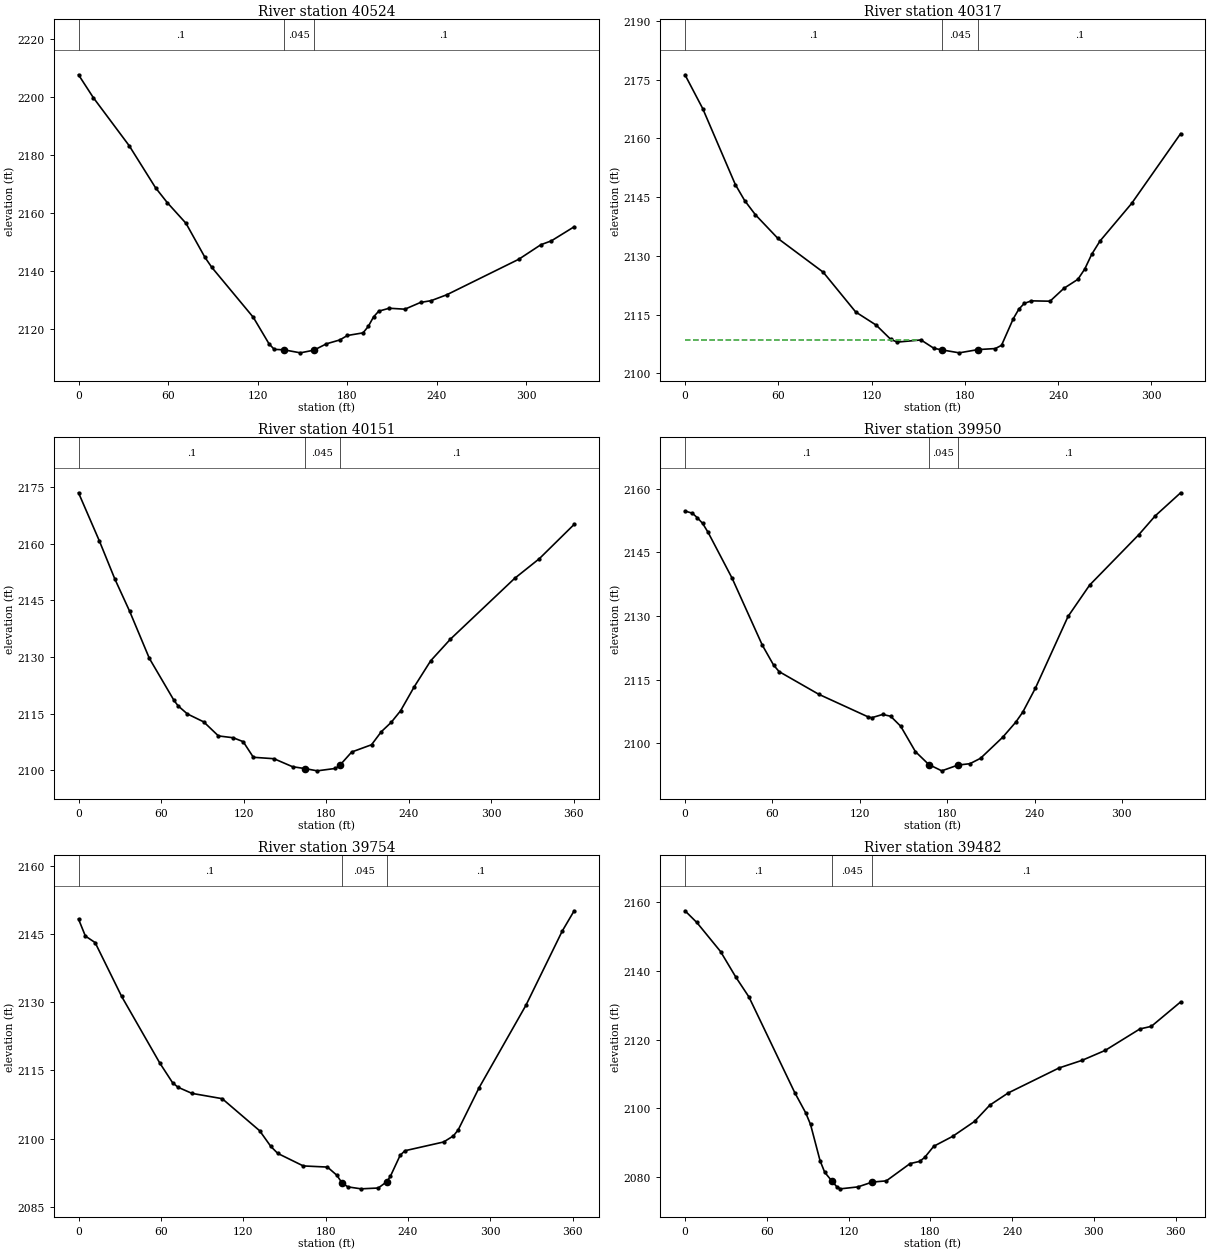
Type RM Length L Ch R = 1 ,40524   ,201.6,207.6,212.4
XS GIS Cut Line= 3
 2065674.7640087308840.8639494632065704.71178344308748.415971622
2065786.74311545 308528.36391829
#Sta/Elev= 30
       0 2207.81     9.9 2199.94      34 2183.31    51.6 2168.85    59.4 2163.76
      72 2156.59    84.6 2144.93    89.2 2141.46   117.1 2124.16   127.6 2115.05
   131.1 2113.13  137.622112.967   148.6 2111.93  157.642112.848   166.1 2115.05
     175 2116.37   180.1 2117.91   190.6 2118.82   194.1 2121.05   197.6 2124.31
   201.1  2126.3   208.1 2127.31   218.6 2126.98   229.1 2129.31   236.2 2129.92
   246.7 2131.96   294.9  2144.2   309.7 2149.21   316.7 2150.54     332  2155.4
#Mann= 3 ,-1 , 0
       0      .1       0  137.62    .045       0  157.64      .1       0
Bank Sta=137.62,157.64
XS Rating Curve= 0 ,0
Exp/Cntr=0.3,0.1

Type RM Length L Ch R = 1 ,40317   ,162,165.8,169.7
XS GIS Cut Line= 2
2065784.13878995308885.1345302162066018.51397735308668.988965124
#Sta/Elev= 30
       0 2176.23    11.4 2167.61    32.4  2148.2    38.4 2144.12    45.3  2140.5
    59.8 2134.45    88.9 2125.85   109.8 2115.69     123 2112.33   132.4 2108.68
   136.6    2108   151.8 2108.55   160.1 2106.42  165.47    2106   176.4 2105.26
  188.69  2106.1   199.6 2106.35   203.6 2107.18   211.2    2114   214.7 2116.38
   218.2 2117.87   222.8 2118.53   234.8 2118.44   243.7 2121.72   252.7 2124.02
   257.1 2126.63   261.6  2130.4   266.9 2133.78   287.3  2143.4   318.8 2161.21
#Mann= 3 ,-1 , 0
       0      .1       0  165.47    .045       0  188.69      .1       0
#XS Ineff= 2 , 0
          149.55 2108.54
Permanent Ineff=
       F       F
Bank Sta=165.47,188.69
XS Rating Curve= 0 ,0
Exp/Cntr=0.3,0.1

Type RM Length L Ch R = 1 ,40151   ,200.7,200.4,197.6
XS GIS Cut Line= 2
2065844.03466752308968.468024954 2066173.4618302308822.634655207
#Sta/Elev= 30
       0 2173.49    15.2  2160.7    26.4 2150.66    37.2 2142.08    51.5 2129.63
    69.4  2118.5    72.4 2117.05    79.1 2114.92      91 2112.81   101.7 2109.09
   112.5  2108.6   119.7 2107.57   127.1 2103.43   142.1 2103.05   155.6 2100.93
   164.72100.435   173.5 2099.84   186.8 2100.48  189.962101.312   198.6 2104.83
     213 2106.75   220.1  2110.2   227.3 2112.68   234.1 2115.74     244 2122.08
     256 2128.99   270.4 2134.74     317 2150.81     335 2156.04   360.3 2165.12
#Mann= 3 ,-1 , 0
       0      .1       0   164.7    .045       0  189.96      .1       0
Bank Sta=164.7,189.96
XS Rating Curve= 0 ,0
Exp/Cntr=0.3,0.1

Type RM Length L Ch R = 1 ,39950   ,194,196.7,200.1
XS GIS Cut Line= 2
2065962.52425995309139.040846542 2066260.7014851308974.978510633
#Sta/Elev= 30
       0 2154.74     5.1 2154.21     8.4 2153.17    12.1 2151.83    15.9 2149.69
    32.4 2138.88    53.1 2123.14    60.8 2118.47    64.6 2116.92    91.8 2111.58
   125.6 2106.27   128.2 2106.05   135.7 2106.82   141.2  2106.4   148.1 2104.05
   158.2 2098.07  167.392095.029   176.3 2093.54   187.42094.899   195.6 2095.22
   202.9 2096.49   218.1 2101.44   227.1    2105   231.9 2107.36   240.6 2113.02
     263  2129.9   277.8 2137.28   311.6 2149.17   322.9 2153.61   340.3 2159.03
#Mann= 3 ,-1 , 0
       0      .1       0  167.39    .045       0   187.4      .1       0
Bank Sta=167.39,187.4
XS Rating Curve= 0 ,0
Exp/Cntr=0.3,0.1

Type RM Length L Ch R = 1 ,39754   ,267,271.7,269.7
XS GIS Cut Line= 2
2066040.64943177309287.4785417912066376.58675203309154.665815294
#Sta/Elev= 30
       0 2148.25       5 2144.52    12.1 2143.09    31.4 2131.28    59.2 2116.65
    68.5 2112.34    72.5 2111.32    82.7 2109.97   104.7 2108.81     132 2101.77
   140.1 2098.34   145.2 2096.79   163.8 2094.04   181.4 2093.79   188.2 2092.01
  192.012090.327   196.3 2089.44   205.9 2089.01   218.4 2089.19  224.552090.546
   227.3 2091.78   234.4 2096.38   237.9 2097.38   266.1  2099.3   273.2 2100.64
   276.7 2101.96   291.8 2111.15   326.1 2129.35   352.5 2145.61   361.2 2150.07
#Mann= 3 ,-1 , 0
       0      .1       0  192.01    .045       0  224.55      .1       0
Bank Sta=192.01,224.55
XS Rating Curve= 0 ,0
Exp/Cntr=0.3,0.1

Type RM Length L Ch R = 1 ,39482   ,187,186.8,186
XS GIS Cut Line= 3
2066063.39249653309486.870859548 2066251.7605581 309420.89855054
2066410.61457109309380.100075707
#Sta/Elev= 30
       0  2157.5     8.7 2154.09    26.1 2145.63    37.4 2138.12    46.9 2132.42
    80.5 2104.57    88.6 2098.63    92.1 2095.28    99.1 2084.72   102.5 2081.35
  107.972078.709   111.4 2077.13     114 2076.53   126.8 2077.09  137.422078.501
   147.7 2078.85   165.1 2083.88   172.1 2084.52   175.8 2085.66   182.5 2088.93
   196.4 2091.82   212.4 2096.16   223.6  2100.9   237.1 2104.45   274.4 2111.73
   291.3 2113.95   308.3 2116.85   333.7 2123.09   342.1 2123.84   363.6 2130.96
#Mann= 3 ,-1 , 0
       0      .1       0  107.97    .045       0  137.42      .1       0
Bank Sta=107.97,137.42
XS Rating Curve= 0 ,0
Exp/Cntr=0.3,0.1

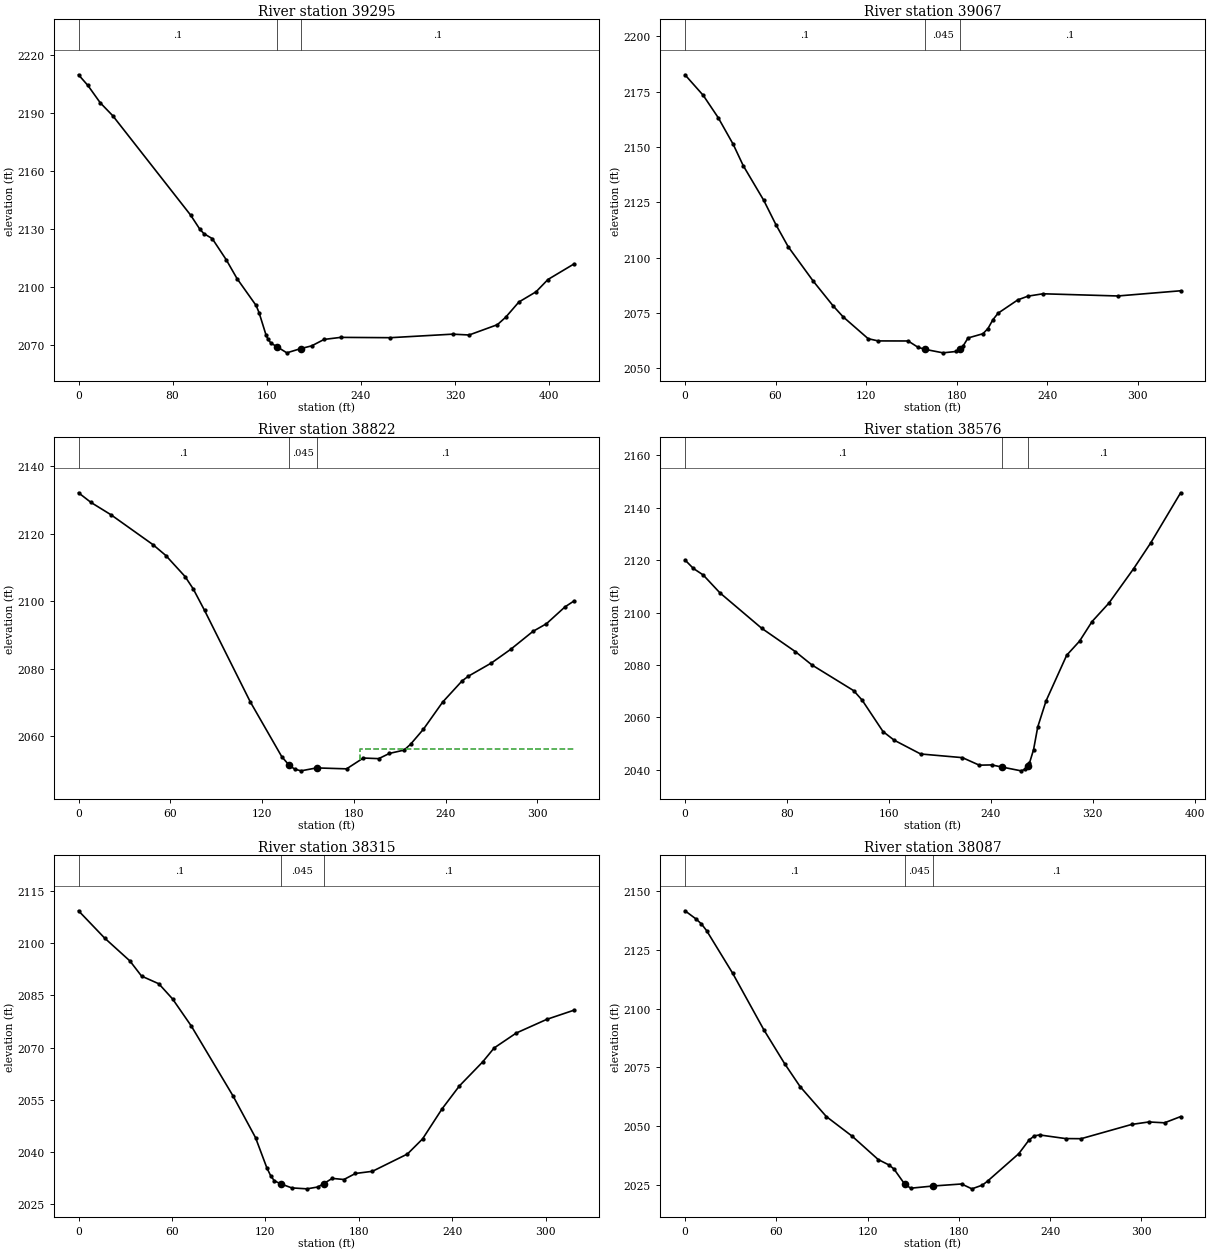
Type RM Length L Ch R = 1 ,39295   ,220,228,231.9
XS GIS Cut Line= 2
2066077.28124827309685.6555669612066469.64234018309532.009548798
#Sta/Elev= 30
       0 2209.93       8 2204.37    18.5 2195.38    29.1  2188.7    95.3 2137.14
   103.1 2129.86   106.6 2127.52   113.7 2124.94   125.6 2113.97   134.8 2104.17
     151 2090.24   153.5 2086.54   159.5 2074.79   161.1 2072.77   163.6 2070.69
  168.852068.818   177.1 2065.68  188.862067.865   198.2 2069.29   208.8 2072.64
   222.9  2073.7   265.2 2073.54     318 2075.37   332.1 2074.94   356.1 2080.28
   363.2 2084.16   374.4 2092.05     389 2097.35   399.1 2103.72   421.4 2111.85
#Mann= 3 ,-1 , 0
       0      .1       0  168.85    .045       0  188.86      .1       0
Bank Sta=168.85,188.86
XS Rating Curve= 0 ,0
Exp/Cntr=0.3,0.1

Type RM Length L Ch R = 1 ,39067   ,256.5,245.4,234.8
XS GIS Cut Line= 2
2066158.01041752309795.8984567082066483.53109193 309840.16936554
#Sta/Elev= 30
       0 2182.64    12.1 2173.34      22 2163.28      32 2151.16    38.6 2141.58
    52.2 2125.91    60.3 2114.86    68.4 2104.93    84.9 2089.47    98.2 2078.18
   104.8 2073.25   121.4 2063.37     128 2062.36   147.9 2062.33   154.5 2059.46
  159.382058.514     171 2056.97   179.8  2057.6  182.152058.577   184.3 2060.03
   187.6 2063.69   197.5 2065.61   200.8 2067.95   204.1 2071.95   207.5 2074.88
   220.6 2080.91   227.3 2082.59   237.3 2083.66   286.9 2082.67   328.5 2085.02
#Mann= 3 ,-1 , 0
       0      .1       0  159.38    .045       0  182.15      .1       0
Bank Sta=159.38,182.15
XS Rating Curve= 0 ,0
Exp/Cntr=0.3,0.1

Type RM Length L Ch R = 1 ,38822   ,231.3,245.7,250.3
XS GIS Cut Line= 2
2066342.03826469310129.2317795462066545.16318652309876.627625957
#Sta/Elev= 30
       0  2132.1     8.2 2129.23    21.3 2125.57    48.7 2116.74    57.1 2113.53
    69.7 2107.29      75 2103.65    82.4 2097.29   112.3 2070.22   132.9 2053.98
  137.522051.551   141.3 2050.29   145.5 2049.78  155.682050.648   175.3 2050.37
   186.2 2053.57   196.3 2053.39   203.3 2054.94   212.9 2055.92   217.1 2057.64
   225.5 2062.08   238.1 2070.13   250.8  2076.4     255 2077.82     270 2081.71
   282.7 2085.79   297.1 2091.05     306 2093.34   318.1 2098.32   324.1  2100.1
#Mann= 3 ,-1 , 0
       0      .1       0  137.52    .045       0  155.68      .1       0
#XS Ineff= 2 , 0
                          184.17         2056.19
Permanent Ineff=
       F       F
Bank Sta=137.52,155.68
XS Rating Curve= 0 ,0
Exp/Cntr=0.3,0.1

Type RM Length L Ch R = 1 ,38576   ,251.3,261.4,261
XS GIS Cut Line= 2
2066368.94798777310144.8567482982066757.83664569310147.461073801
#Sta/Elev= 30
       0 2120.09     6.6 2116.84    14.3 2114.35    27.4 2107.53    60.2 2093.99
    86.5 2085.11    99.6 2079.98   132.4 2070.15     139 2066.54   155.4 2054.53
   164.1 2051.25   184.9 2045.97   217.7 2044.57   230.9  2041.7   240.7 2041.79
  248.372041.012   263.7 2039.53   266.9 2040.13   268.92041.434   270.2 2042.34
   273.5 2047.61   276.8 2056.32   283.3 2066.24   299.5 2083.69   309.6 2089.08
   319.4 2096.56   332.6 2103.59   352.1 2116.81   365.4 2126.58   388.9 2145.75
#Mann= 3 ,-1 , 0
       0      .1       0  248.37    .045       0   268.9      .1       0
Bank Sta=248.37,268.9
XS Rating Curve= 0 ,0
Exp/Cntr=0.3,0.1

Type RM Length L Ch R = 1 ,38315   ,234.2,228,216.9
XS GIS Cut Line= 2
2066367.21177077310275.0651492922066648.46186444310424.370624959
#Sta/Elev= 30
       0  2109.4    16.7 2101.57      33 2094.95    40.5 2090.58    51.6 2088.36
    60.4 2084.01    72.5 2076.16    99.2 2056.09   113.7 2044.04     121  2035.3
   123.4 2033.08   125.8 2031.58  129.972030.699     137 2029.54   146.8 2029.27
   153.8 2029.81   157.4 2030.75     163 2032.28   170.5 2031.96   177.9  2033.7
   188.8 2034.32   211.3 2039.31     221 2043.65   233.6 2052.36   244.7 2058.94
   259.6 2065.83     267 2069.87   281.2 2074.17   300.8 2078.11   318.4 2080.77
#Mann= 3 , 0 , 0
       0      .1       0  129.97    .045       0   157.4      .1       0
Bank Sta=129.97,157.4
XS Rating Curve= 0 ,0
Exp/Cntr=0.3,0.1

Type RM Length L Ch R = 1 ,38087   ,213.4,211.9,206.2
XS GIS Cut Line= 2
 2066307.3158932310603.1901492182066619.81592435310511.176225632
#Sta/Elev= 30
       0  2141.5     7.3 2138.01    10.8 2135.93    14.2 2133.09    31.3 2115.04
    51.8 2091.04    65.5 2076.63    75.7 2066.87    92.9 2054.19   109.9 2045.84
     127 2035.95   133.9  2033.7   137.3 2031.99  144.472025.461   148.4 2023.78
  162.882024.703   181.8 2025.57   188.6 2023.51   195.5 2025.09   198.9 2026.79
   219.4 2038.43   226.2 2044.27   229.7    2046   233.1 2046.38   250.2 2044.84
   260.4 2044.79   293.7 2050.85   304.9 2051.89   315.2 2051.53   325.8 2054.17
#Mann= 3 ,-1 , 0
       0      .1       0  144.47    .045       0  162.88      .1       0
Bank Sta=144.47,162.88
XS Rating Curve= 0 ,0
Exp/Cntr=0.3,0.1

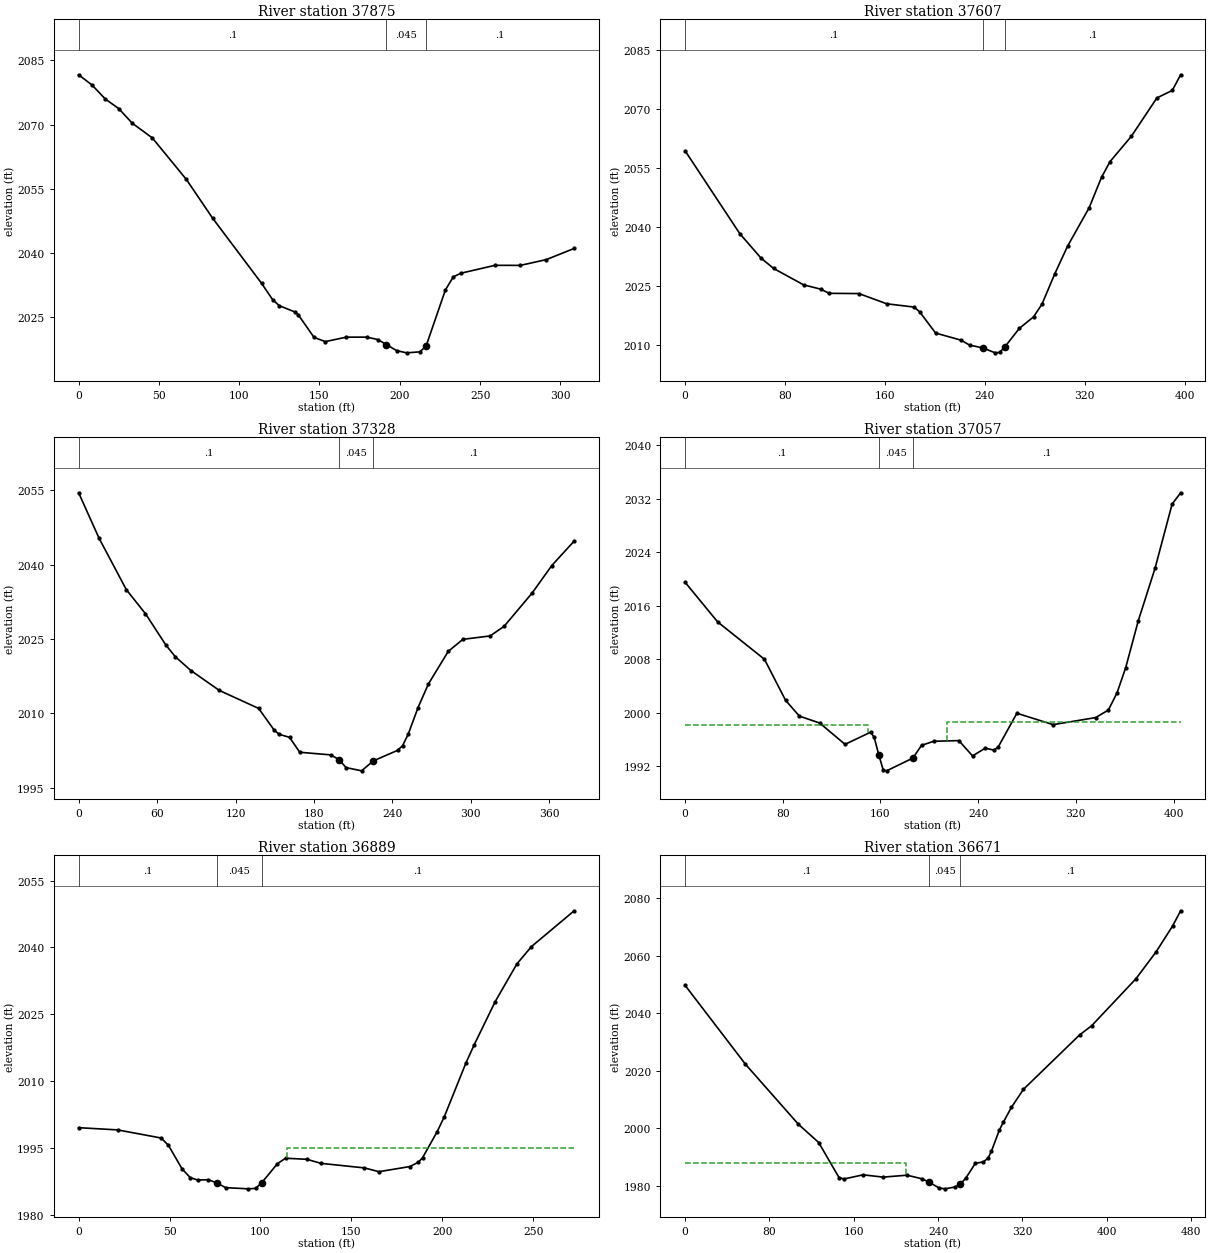
Type RM Length L Ch R = 1 ,37875   ,257.5,267.9,274.9
XS GIS Cut Line= 2
2066419.29499993310851.4540883752066662.35061619310661.349809796
#Sta/Elev= 30
       0 2081.65     8.4 2079.23    16.7 2075.95      25 2073.73    33.4 2070.31
    45.9 2066.87    67.1 2057.15    83.4  2048.1   113.9 2032.85   120.9 2028.96
     125 2027.59   134.9  2026.1   136.9 2025.41   146.6 2020.18   153.6 2019.19
   166.7 2020.23   179.5 2020.24   186.3 2019.67  191.642018.499     198 2017.09
   204.2 2016.56   212.5 2016.79  216.362018.131   228.4 2031.27   233.3 2034.34
     238 2035.19   259.3 2037.05   275.1 2037.03   291.3 2038.39   308.6    2041
#Mann= 3 ,-1 , 0
       0      .1       0  191.64    .045       0  216.36      .1       0
Bank Sta=191.64,216.36
XS Rating Curve= 0 ,0
Exp/Cntr=0.3,0.1

Type RM Length L Ch R = 1 ,37607   ,275.2,279.3,281.9
XS GIS Cut Line= 2
2066459.22569436310879.2319199592066841.17014045310986.870812297
#Sta/Elev= 30
       0 2059.37    43.8 2038.34    60.8 2032.14    70.9 2029.51    94.9 2025.35
   108.6 2024.26   115.4  2023.2   139.2 2023.14   161.4 2020.55   183.5 2019.71
     188 2018.43   200.6 2013.12     221 2011.31   227.8 2010.06  238.322009.357
   248.3  2008.1   251.8  2008.2   255.82009.508   267.7 2014.33     279 2017.22
   285.8 2020.47     296 2028.14   306.3 2035.18   323.6 2044.96   333.5 2052.68
   340.3 2056.64   357.4 2063.08   377.8 2072.79   390.1 2074.68   396.8 2078.66
#Mann= 3 ,-1 , 0
       0      .1       0  238.32    .045       0   255.8      .1       0
Bank Sta=238.32,255.8
XS Rating Curve= 0 ,0
Exp/Cntr=0.3,0.1

Type RM Length L Ch R = 1 ,37328   ,276.9,270.7,250.7
XS GIS Cut Line= 2
2066406.27435669311080.6206247962066722.24649379311289.822306126
#Sta/Elev= 30
       0 2054.47    15.7 2045.26    36.5 2034.92    51.1 2030.08    66.8 2023.73
      74 2021.38    85.9 2018.61   107.6  2014.6   137.7 2010.97   149.5 2006.61
   153.4 2005.74   161.3 2005.14   169.1 2002.13   192.7  2001.6  199.282000.645
   204.5 1999.04   216.4 1998.38  225.41 2000.39   243.9 2002.51   247.8 2003.48
     252 2005.73   259.6 2011.15   267.5  2015.9   282.7 2022.48   293.9 2024.91
   314.7 2025.59   325.4 2027.53   346.7  2034.2   361.9  2039.8     379 2044.73
#Mann= 3 ,-1 , 0
       0      .1       0  199.28    .045       0  225.41      .1       0
Bank Sta=199.28,225.41
XS Rating Curve= 0 ,0
Exp/Cntr=0.3,0.1

Type RM Length L Ch R = 1 ,37057   ,169.8,168.2,162
XS GIS Cut Line= 2
2066305.58000427311477.3222592182066688.39223078311342.773643792
#Sta/Elev= 30
       0 2019.51    26.7 2013.57      65 2007.99    82.3 2001.85    93.6 1999.49
   110.2 1998.46     131 1995.27   151.9 1997.09   154.8 1996.33  158.741993.623
   162.3  1991.4     165 1991.31  186.521993.217   193.6 1995.12   203.6 1995.73
   224.2 1995.83   235.4 1993.54   245.8  1994.7   252.7 1994.42   256.2 1994.81
   271.7 1999.92   301.4 1998.22   336.2 1999.27   346.6  2000.4   353.6 2002.92
   360.8 2006.73   371.1 2013.74   384.9 2021.64   398.8 2031.19   405.8 2032.89
#Mann= 3 ,-1 , 0
       0      .1       0  158.74    .045       0  186.52      .1       0
#XS Ineff= 2 ,-1
       0  149.97  1998.1   214.2  405.77 1998.54
Permanent Ineff=
       F       F
Bank Sta=158.74,186.52
XS Rating Curve= 0 ,0
Exp/Cntr=0.3,0.1

Type RM Length L Ch R = 1 ,36889   ,216.6,217.5,218.1
XS GIS Cut Line= 2
2066487.00352594311606.6625517162066710.96173945311451.280644625
#Sta/Elev= 30
       0 1999.54    21.5 1999.04    45.4 1997.22    49.4 1995.58    56.9 1990.28
    61.4 1988.33    65.4  1987.8    71.4 1987.85   76.281987.103    80.8 1986.08
    93.4 1985.81    97.3 1985.91   100.61987.112   109.3 1991.43   113.8 1992.68
   125.6 1992.44   133.3 1991.53   157.2 1990.51   165.2 1989.66   182.2 1990.81
   186.9 1991.79   189.2  1992.8   197.2 1998.61   201.2 2002.04   213.1 2014.11
   217.5 2018.06   229.1  2027.8   241.1 2036.31   249.1 2040.19   272.6 2048.23
#Mann= 3 ,-1 , 0
       0      .1       0   76.28    .045       0   100.6      .1       0
#XS Ineff= 1 ,-1
  114.43  272.58 1995.04
Permanent Ineff=
       F
Bank Sta=76.28,100.6
XS Rating Curve= 0 ,0
Exp/Cntr=0.3,0.1

Type RM Length L Ch R = 1 ,36671   ,293,291.9,285.5
XS GIS Cut Line= 2
2066457.48947737311864.4750282172066862.87154061311626.627734885
#Sta/Elev= 30
       0  2049.7    57.2 2022.33   107.5 2001.45   126.7 1995.13     146 1982.95
   150.7 1982.46   168.8 1983.91   187.8 1983.11   210.6 1983.78     225 1982.49
  231.741981.272   241.1 1979.31   246.5 1979.04   256.3  1979.7  261.111980.687
   266.1 1982.69   275.3 1987.91   282.9 1988.39   287.3 1989.68   290.5 1992.07
   298.1 1999.49   301.9 2002.23   309.5 2007.34   320.9 2013.59   374.2  2032.5
   385.6 2035.68   427.5 2051.95   446.5 2061.22   462.3 2070.27     470  2075.6
#Mann= 3 , 0 , 0
       0      .1       0  231.74    .045       0  261.11      .1       0
#XS Ineff= 2 , 0
          209.68 1987.89
Permanent Ineff=
       F       F
Bank Sta=231.74,261.11
XS Rating Curve= 0 ,0
Exp/Cntr=0.3,0.1

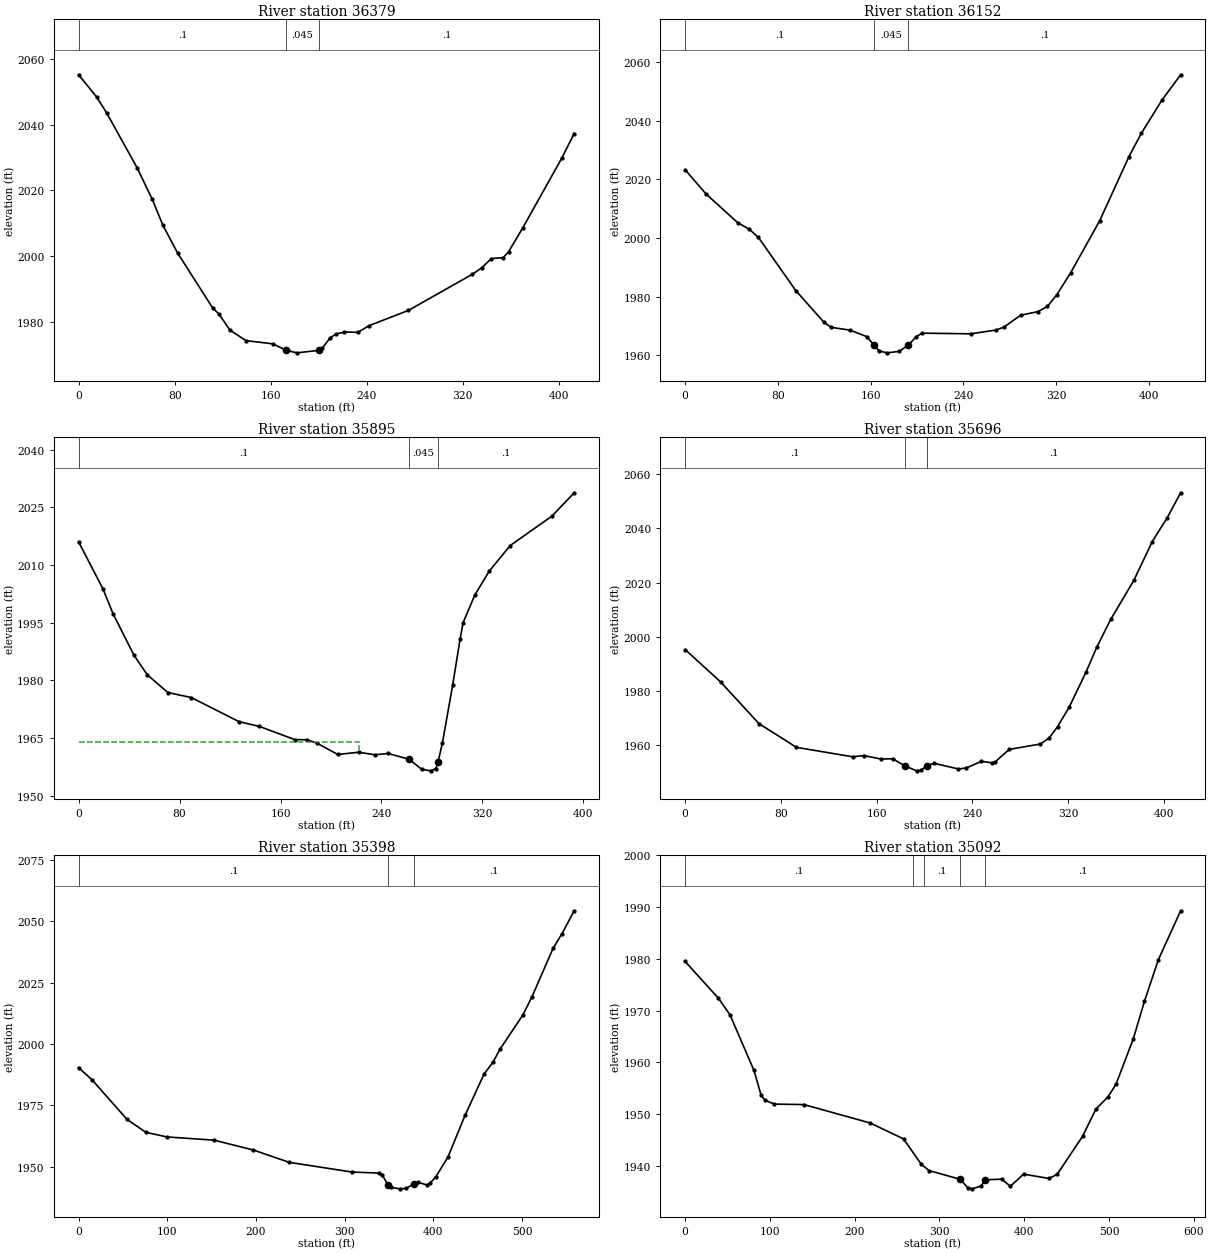
Type RM Length L Ch R = 1 ,36379   ,230.3,227.2,219.8
XS GIS Cut Line= 2
2066625.80541369312149.110285714 2066905.7533446311845.725065708
#Sta/Elev= 30
       0  2055.3    14.9 2048.58    23.3  2043.7    48.7 2026.93    61.1 2017.48
    70.3 2009.31    82.6 2000.82   111.6 1984.17   117.1 1982.19     126  1977.4
   139.4 1974.18   161.7  1973.2  172.92 1971.23   181.8 1970.45  199.851971.189
   202.7  1971.8   209.6 1975.03   214.3 1976.18   221.3 1976.81   232.6 1976.71
   242.1 1978.77   274.7 1983.39   328.1 1994.46   335.8 1996.39   343.8 1999.21
   353.7 1999.51   358.1 2001.27   369.9 2008.53   402.4  2029.8   412.8 2037.38
#Mann= 3 ,-1 , 0
       0      .1       0  172.92    .045       0  199.85      .1       0
Bank Sta=172.92,199.85
XS Rating Curve= 0 ,0
Exp/Cntr=0.3,0.1

Type RM Length L Ch R = 1 ,36152   ,246.9,257.1,257.7
XS GIS Cut Line= 2
2066840.64914411312320.985270038 2067013.8262912311930.360395134
#Sta/Elev= 30
       0 2023.33    17.9 2015.13    45.3 2005.28    55.2 2003.08    63.2 2000.24
    95.5  1982.1   119.8 1971.26   126.2 1969.55   142.2 1968.62   156.5 1966.42
  163.091963.499   167.3 1961.48   174.5 1960.87   184.5 1961.37  192.441963.467
   199.4 1966.43   204.4 1967.58   246.2 1967.36   267.8 1968.62   274.9 1969.62
   289.3  1973.7   304.3 1974.94   312.4  1976.7   320.5 1980.67   332.4 1988.14
   357.5 2005.93   382.6  2027.7   393.4 2035.76   411.3 2047.14   427.3 2055.72
#Mann= 3 ,-1 , 0
       0      .1       0  163.09    .045       0  192.44      .1       0
Bank Sta=163.09,192.44
XS Rating Curve= 0 ,0
Exp/Cntr=0.3,0.1

Type RM Length L Ch R = 1 ,35895   ,201,199.2,197
XS GIS Cut Line= 2
2066929.19096178312396.5061163752067240.38883018 312156.92293413
#Sta/Elev= 30
       0 2016.02    19.3 2003.79    27.3 1997.33    43.9 1986.53    54.3  1981.5
    70.7 1976.85    89.4 1975.53   127.1 1969.27   143.3 1968.03   171.3  1964.6
   180.9 1964.57   188.8  1963.7   205.4 1960.73   221.9 1961.32   234.7 1960.66
   245.4 1960.99  261.831959.498   271.9 1956.88   278.9 1956.48   283.1 1957.06
  284.74  1958.7   288.2  1963.6   296.5 1978.93   302.3 1990.76   304.7 1995.04
     314 2002.23   325.4 2008.43     342 2015.08   375.1 2022.73   392.7  2028.8
#Mann= 3 , 0 , 0
       0      .1       0  261.83    .045       0  284.74      .1       0
#XS Ineff= 2 , 0
          222.52 1964.07
Permanent Ineff=
       F       F
Bank Sta=261.83,284.74
XS Rating Curve= 0 ,0
Exp/Cntr=0.3,0.1

Type RM Length L Ch R = 1 ,35696   ,301.9,297.6,296.2
XS GIS Cut Line= 3
2067111.48259193312563.1727778022067222.81307793312402.850919962
2067338.04513094312216.818811715
#Sta/Elev= 30
       0 1995.21    29.7  1983.2    61.6 1967.82      93 1959.01   140.2  1955.5
   149.5 1955.97   163.8 1954.66   173.5 1954.79   183.31952.204   193.4 1950.31
   197.4 1950.54  201.72 1952.24   208.3 1953.07   228.2 1951.01   234.9 1951.36
   247.5 1953.82   256.4 1953.28   259.1 1953.66   270.8 1958.24   296.9 1960.25
     304 1962.41   311.2 1966.66   320.9  1973.9     335 1986.88     344 1996.16
   355.6 2006.36   374.9 2020.79   390.3 2035.15   402.7 2043.91     414 2053.21
#Mann= 3 ,-1 , 0
       0      .1       0   183.3    .045       0  201.72      .1       0
Bank Sta=183.3,201.72
XS Rating Curve= 0 ,0
Exp/Cntr=0.3,0.1

Type RM Length L Ch R = 1 ,35398   ,297.6,306,312.9
XS GIS Cut Line= 3
2067428.32283753312822.5046082142067510.99491626312470.140155464
2067559.83340126 312279.53554979
#Sta/Elev= 30
       0  1990.3    15.1 1985.39    54.4 1969.29    75.7 1963.99    99.3  1962.1
   152.7 1960.78   197.1 1956.75   237.3 1951.75   308.3 1947.78   338.6 1947.37
     342 1946.73  348.891942.531   352.1 1941.56   361.9 1940.94     369  1941.1
  378.331943.028   382.5  1943.6   392.7 1942.53   396.1 1943.17   402.8 1945.92
   416.4 1953.89   435.6 1970.84     457 1987.65   467.2 1992.57   474.9 1997.75
     501 2011.87   511.2 2019.28   534.9 2038.96   545.1    2045   558.7 2054.26
#Mann= 3 , 0 , 0
       0      .1       0  348.89    .045       0  378.33      .1       0
Bank Sta=348.89,378.33
XS Rating Curve= 0 ,0
Exp/Cntr=0.3,0.1

Type RM Length L Ch R = 1 ,35092   ,292.8,283.7,269.9
XS GIS Cut Line= 3
 2067516.8646552312878.4939975442067881.44791552312506.098088801
2067919.20833868312455.317022383
#Sta/Elev= 30
       0 1979.48    39.2 1972.39      53 1969.16    81.2 1958.44    89.7 1953.61
    94.3 1952.64   105.4 1951.92   140.2 1951.83   218.3 1948.27   257.6  1945.2
   278.4 1940.33   287.7 1939.08  324.491937.392   333.1  1935.8   338.8 1935.55
   349.3 1936.12  353.991937.297   373.6 1937.42   383.6 1936.04   399.1 1938.39
     429 1937.56   438.7 1938.33   468.7 1945.69   484.6 1950.99   498.4 1953.25
   508.1 1955.72   528.6 1964.55   541.7 1971.77   558.1 1979.81   584.4 1989.27
#Mann= 5 ,-1 , 0
       0      .1       0  268.18      .1       0  282.08      .1       0
  324.49    .045       0  353.99      .1       0
Bank Sta=324.49,353.99
XS Rating Curve= 0 ,0
Exp/Cntr=0.3,0.1