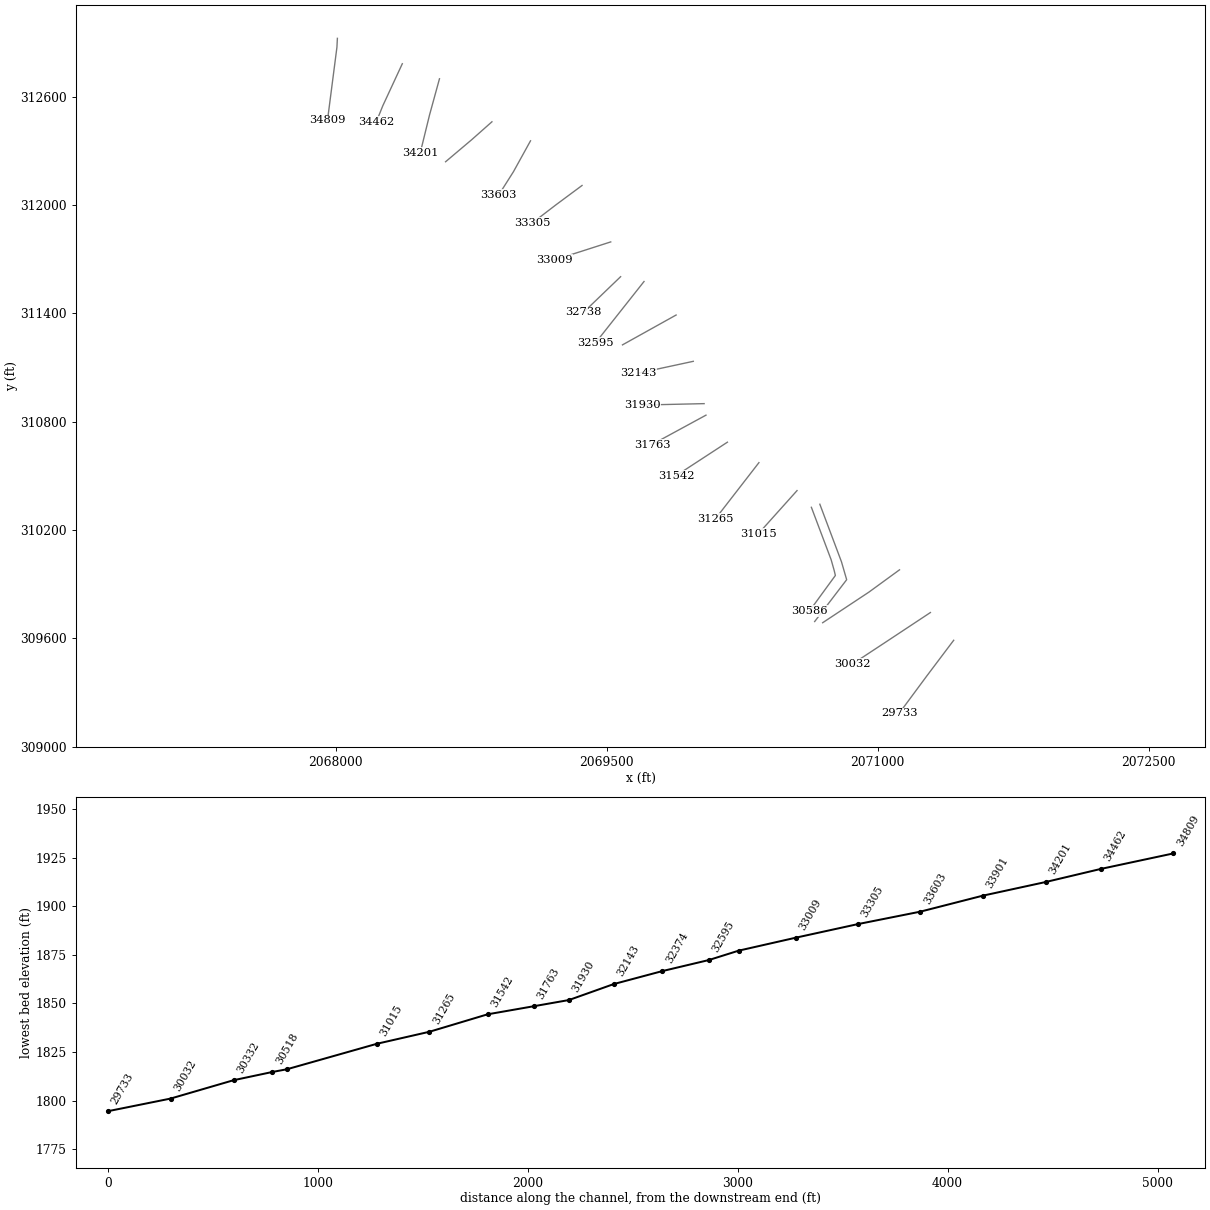
HEC-RAS study KTCHNCK.prj: KTCHNCK

--- KTCHNCK.g01 (geometry) --- (continued)

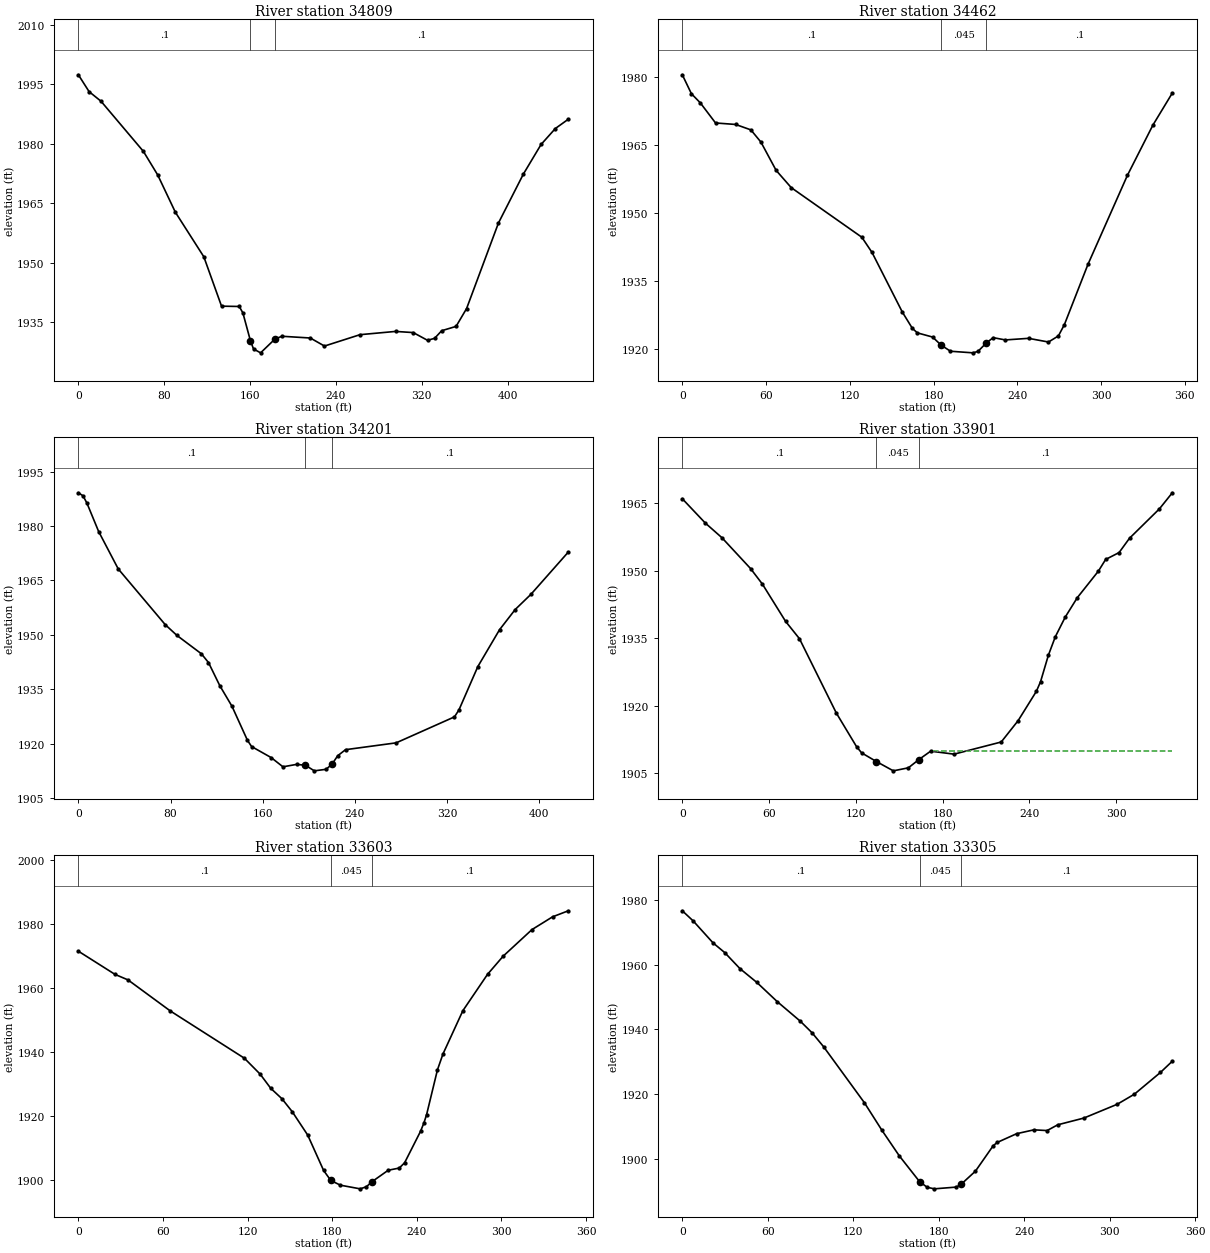
Type RM Length L Ch R = 1 ,34809   ,346.5,346.4,340.4
XS GIS Cut Line= 3
2068009.05199102312924.0670691282068006.44799361312874.587837383
2067954.36443636312470.941991121
#Sta/Elev= 30
       0 1997.37      10 1993.12    21.1  1990.7    60.6 1978.05    73.9 1972.12
    90.4  1962.7   116.9 1951.47   133.4 1939.02   149.9 1938.94   153.3 1937.31
  160.251930.354   163.2 1928.22   169.8 1927.25  183.041930.698   189.6 1931.43
   216.1 1930.99   229.3 1928.96   262.4 1931.83   295.5 1932.65     312 1932.36
   325.3 1930.41   331.9 1930.91   338.5 1932.83   351.9 1933.92   361.7 1938.42
   391.4    1960   414.6 1972.33   431.1  1979.8   444.4 1983.82   456.5 1986.17
#Mann= 3 ,-1 , 0
       0      .1       0  160.25    .045       0  183.04      .1       0
Bank Sta=160.25,183.04
XS Rating Curve= 0 ,0
Exp/Cntr=0.3,0.1

Type RM Length L Ch R = 1 ,34462   ,258.3,261,262.7
XS GIS Cut Line= 3
2068368.42692843312783.4420222942068260.35430995312550.368997633
 2068225.1978842312463.129342705
#Sta/Elev= 30
       0 1980.42     6.5 1976.26    12.9 1974.24    23.8 1969.82    38.2 1969.49
    49.1  1968.3    56.3 1965.62    67.2 1959.39      78  1955.6   128.6 1944.68
   135.9 1941.33   157.6 1928.22   164.8 1924.63   168.4 1923.64   179.3 1922.72
  185.371920.957   192.1  1919.6   208.2 1919.25   211.8 1919.57  217.871921.453
   222.7 1922.59   231.4 1922.09     248 1922.44   262.3 1921.63   269.4 1922.97
   273.7 1925.46   290.6 1938.73   318.9 1958.34   337.1 1969.35     351  1976.4
#Mann= 3 ,-1 , 0
       0      .1       0  185.37    .045       0  217.87      .1       0
Bank Sta=185.37,217.87
XS Rating Curve= 0 ,0
Exp/Cntr=0.3,0.1

Type RM Length L Ch R = 1 ,34201   ,306.2,300,289.9
XS GIS Cut Line= 3
2068574.15617576312700.1085275412068519.32098362312500.420934796
2068467.38539195312288.650360957
#Sta/Elev= 30
       0 1989.16       4 1988.34     7.4 1986.34    17.6 1978.49    34.6 1968.18
    75.4 1952.82    85.6 1949.84   106.7 1944.81   112.9 1942.39   122.7 1936.02
   133.3 1930.33   146.7 1920.96   150.3 1919.24   167.3  1916.2   177.5 1913.66
   189.4 1914.33  197.061914.082   204.7 1912.55   214.9 1912.97   220.11914.393
     225 1916.71   231.8 1918.38   275.7 1920.26   326.3 1927.42   330.2 1929.34
   346.6 1941.29   365.4 1951.43     379    1957   392.6 1961.17   425.1 1972.84
#Mann= 3 ,-1 , 0
       0      .1       0  197.06    .045       0   220.1      .1       0
Bank Sta=197.06,220.1
XS Rating Curve= 0 ,0
Exp/Cntr=0.3,0.1

Type RM Length L Ch R = 1 ,33901   ,292.6,297.9,302.1
XS GIS Cut Line= 3
2068864.52075252312461.8275080472068754.26211476312364.107887208
2068608.01043877312240.473291963
#Sta/Elev= 30
       0 1965.99    15.9 1960.59    27.4 1957.33    47.2 1950.47    55.4 1947.01
    71.4 1938.74      81 1934.88   106.5 1918.35   120.5 1910.87     124  1909.5
  134.231907.572   145.9 1905.51   156.3 1906.18  163.561908.013   171.7 1909.88
   187.9 1909.22   220.5 1911.92   232.2 1916.67   244.8 1923.18   247.7 1925.33
   253.1  1931.2   257.9 1935.31   264.8 1939.71   273.1    1944   287.7 1949.91
   292.7  1952.5     302 1954.03   309.2 1957.21   329.9 1963.75   338.8 1967.32
#Mann= 3 ,-1 , 0
       0      .1       0  134.23    .045       0  163.56      .1       0
#XS Ineff= 2 , 0
                          173.32         1910.03
Permanent Ineff=
       F       F
Bank Sta=134.23,163.56
XS Rating Curve= 0 ,0
Exp/Cntr=0.3,0.1

Type RM Length L Ch R = 1 ,33603   ,305.1,298.4,293.7
XS GIS Cut Line= 3
2069078.06264827312356.3585588782068983.67799452312185.415987372
 2068902.2811757312056.879499048
#Sta/Elev= 30
       0  1971.5      26 1964.25    35.2 1962.53    65.2 1952.83   117.7 1938.07
   128.9 1933.09   136.4 1928.67   144.3 1925.43   151.6 1921.39   162.6 1914.07
   173.9    1903     179 1899.88   185.8 1898.41   199.8 1897.27   204.2 1897.92
  208.221899.508   219.7 1903.08   227.5 1903.76   231.3  1905.4   242.6 1915.23
     245 1917.85   246.9 1920.45   254.6 1934.45   258.5 1939.38   272.6  1952.9
   290.1 1964.27   301.2 1969.95   321.6 1978.24   336.2 1982.23   347.4 1984.12
#Mann= 3 ,-1 , 0
       0      .1       0     179    .045       0  208.22      .1       0
Bank Sta=179,208.22
XS Rating Curve= 0 ,0
Exp/Cntr=0.3,0.1

Type RM Length L Ch R = 1 ,33305   ,299.9,295.9,289.6
XS GIS Cut Line= 3
2069363.21857402312108.962728217 2069218.9380227312001.917010546
2069088.47929412311901.931646213
#Sta/Elev= 30
       0 1976.57     7.7 1973.41    21.6 1966.66    29.8 1963.67    40.5 1958.72
    52.3 1954.49    66.6 1948.58    82.9  1942.5    91.1 1938.95    99.2 1934.65
   127.8 1917.41   140.1 1908.92   152.3 1901.03  166.591893.051   171.9 1891.32
   176.9 1890.84   192.4 1891.38  195.771892.254   205.8  1896.3   218.2  1904.1
     221 1905.13   234.7 1907.84   246.8 1909.03   256.1 1908.81   263.6 1910.59
   281.9 1912.66   305.3 1916.91   317.4 1920.03   335.7 1926.74     344 1930.19
#Mann= 3 ,-1 , 0
       0      .1       0  166.59    .045       0  195.77      .1       0
Bank Sta=166.59,195.77
XS Rating Curve= 0 ,0
Exp/Cntr=0.3,0.1

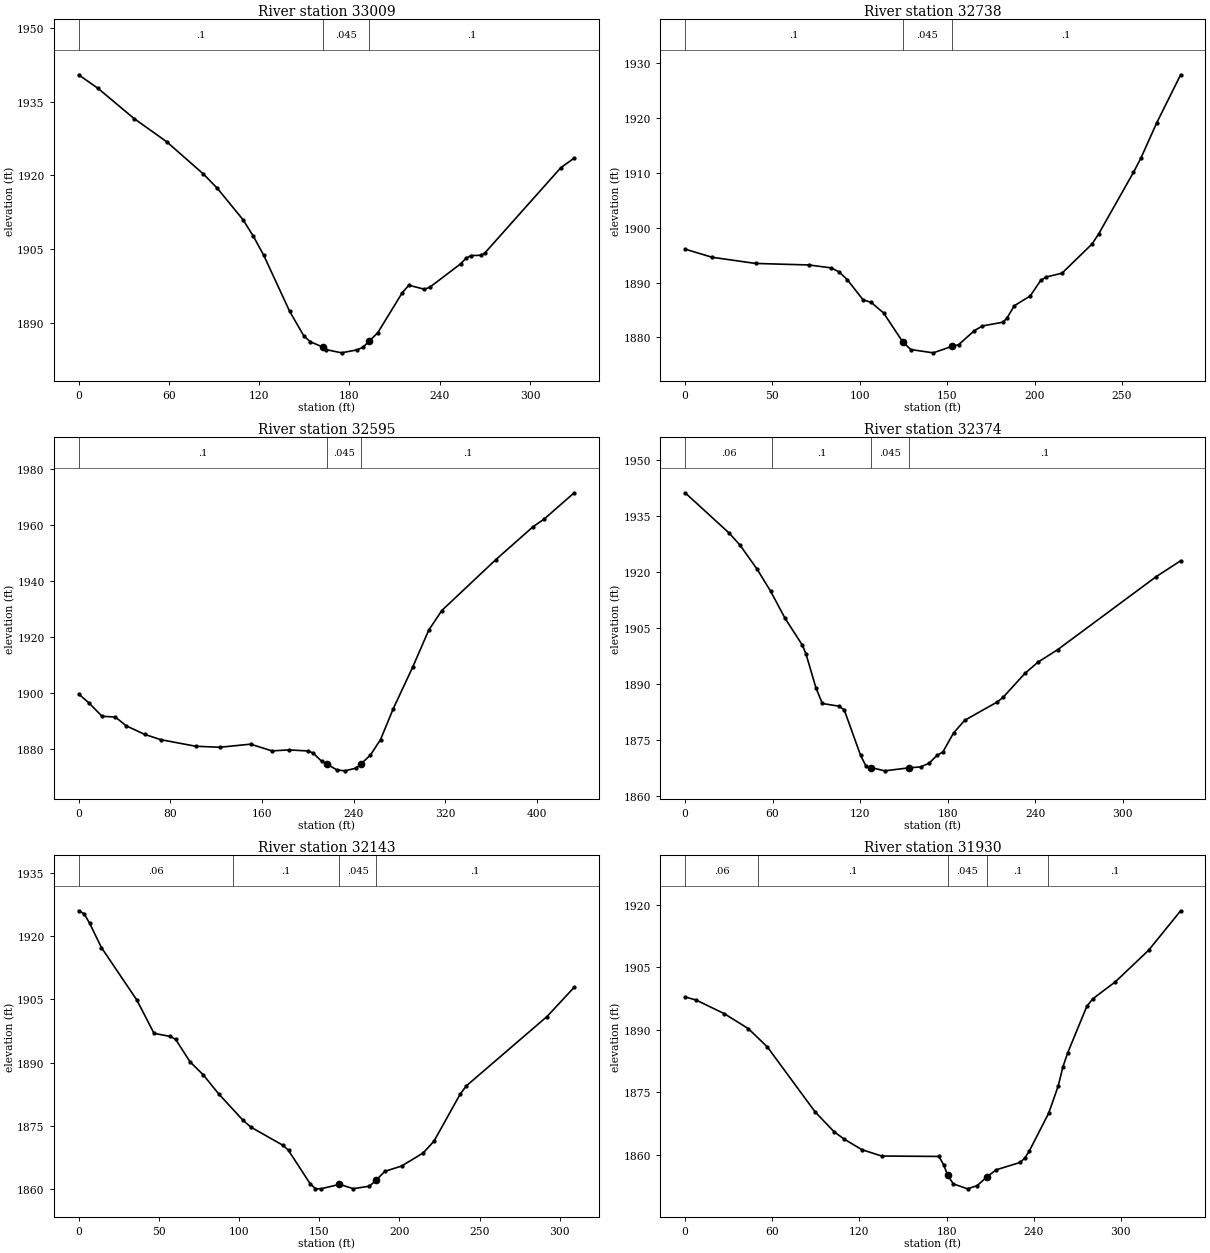
Type RM Length L Ch R = 1 ,33009   ,265.2,271.1,278.3
XS GIS Cut Line= 3
2069522.07291511311796.4626970442069356.66510943 311743.27710788
 2069208.2707212311696.202398881
#Sta/Elev= 30
       0  1940.5    12.8 1937.75    36.9 1931.57    58.5 1926.86    82.9 1920.29
    92.1  1917.4   109.3 1910.96   116.2 1907.57   123.1 1903.68   140.3 1892.28
   149.8 1887.24   154.1 1886.08  162.111885.049   164.4 1884.51   174.8 1883.84
   185.1 1884.45     189 1884.98  193.21 1886.23   198.9 1887.96   215.1 1896.08
   219.5 1897.62   229.8  1896.8   233.3 1897.18   253.9 1901.97   257.4 1903.09
   260.8 1903.66   267.4 1903.72     270 1904.18   320.5 1921.56   329.4 1923.52
#Mann= 3 ,-1 , 0
       0      .1       0  162.11    .045       0  193.21      .1       0
Bank Sta=162.11,193.21
XS Rating Curve= 0 ,0
Exp/Cntr=0.3,0.1

Type RM Length L Ch R = 1 ,32738   ,139.8,142.3,143.9
XS GIS Cut Line= 3
2069576.76046976 311603.75442104 2069473.8958461 311504.79595755
 2069372.3333852311407.139984876
#Sta/Elev= 30
       0 1896.11    15.4 1894.63    40.3  1893.5      71 1893.22    83.7 1892.68
    88.2 1891.93    92.8 1890.54   101.9 1886.85   106.4 1886.41   113.6 1884.47
  124.791879.077   129.2 1877.79     142 1877.19  152.571878.354   156.5 1878.67
   165.6 1881.25   170.2  1882.1   181.9 1882.78   184.2 1883.52   188.4 1885.78
   197.5 1887.56   203.5 1890.39   206.6 1891.02   215.7 1891.72   232.9 1897.05
   236.6 1898.84   256.6 1910.11   260.8 1912.68     270 1919.21   283.6 1927.92
#Mann= 3 ,-1 , 0
       0      .1       0  124.79    .045       0  152.57      .1       0
Bank Sta=124.79,152.57
XS Rating Curve= 0 ,0
Exp/Cntr=0.3,0.1

Type RM Length L Ch R = 1 ,32595   ,226,221.2,217.2
XS GIS Cut Line= 2
2069706.36626547311577.0929037042069438.30985318311237.960927548
#Sta/Elev= 30
       0 1899.71     8.8 1896.65    20.4  1891.8    32.1 1891.53    41.3 1888.44
    57.6 1885.34    71.8 1883.45   102.2 1881.11   123.2 1880.76     150 1881.86
   168.7 1879.46   183.5 1879.81   200.2 1879.43   204.4 1878.74     212 1875.76
   217.11874.623   225.3 1872.68   232.2 1872.35     242 1873.31   246.2 1874.75
   254.6 1878.01   263.4 1883.51   274.5 1894.53   291.4 1909.29   305.4 1922.48
   316.8 1929.49   363.8 1947.58   396.5  1959.4   405.9 1962.02   432.3 1971.47
#Mann= 3 ,-1 , 0
       0      .1       0   217.1    .045       0   246.2      .1       0
Bank Sta=217.1,246.2
XS Rating Curve= 0 ,0
Exp/Cntr(USF)=0,0
Exp/Cntr=0.3,0.1

Type RM Length L Ch R = 1 ,32374   ,235.8,231.1,228
XS GIS Cut Line= 2
2069884.05217803311391.5150161242069587.17711562311226.150189385
#Sta/Elev= 30
       0 1941.32    30.2 1930.51    37.7 1927.24    49.3 1920.85    58.7 1914.85
    68.4 1907.72    80.4 1900.41    82.9 1898.06    89.7 1888.97    94.1 1884.75
   105.3 1884.04   109.1 1883.05   120.3 1870.87   124.1  1867.9  127.431867.559
   136.9 1866.67   153.41867.471   161.6 1867.73   167.3 1868.72   172.9 1870.88
   176.7 1871.69   184.1 1876.84   191.7 1880.23   214.2 1885.19   218.2 1886.46
     233 1892.83     242 1895.85   255.5 1899.21   323.1 1918.82   339.8 1923.07
#Mann= 4 ,-1 , 0
       0     .06       0    59.6      .1       0  127.43    .045       0
   153.4      .1       0
Bank Sta=127.43,153.4
XS Rating Curve= 0 ,0
Exp/Cntr=0.3,0.1

Type RM Length L Ch R = 1 ,32143   ,215.6,213.7,210.1
XS GIS Cut Line= 2
2069979.10415328311135.0043742952069677.02076793311069.900173798
#Sta/Elev= 30
       0 1926.05     3.4 1925.34     6.8 1923.13    14.2 1917.32    36.3 1904.85
      47 1896.94    57.1  1896.2    60.5 1895.51    69.4  1890.2    77.7 1887.08
    87.3 1882.57   102.5 1876.29   107.4 1874.66   127.6  1870.3   130.9 1869.12
   144.4 1861.18   147.7 1860.04   151.1    1860  162.641861.074   171.2 1860.04
   181.3 1860.63  185.411862.005   190.9 1864.15   201.4 1865.42   214.8 1868.51
   221.6 1871.33   237.8 1882.42   241.7 1884.44     292 1900.91     309 1907.86
#Mann= 4 ,-1 , 0
       0     .06       0   96.04      .1       0  162.64    .045       0
  185.41      .1       0
Bank Sta=162.64,185.41
XS Rating Curve= 0 ,0
Exp/Cntr=0.3,0.1

Type RM Length L Ch R = 1 ,31930   ,157,166.6,169.7
XS GIS Cut Line= 2
2070039.00003085310900.6295149622069697.85405961310892.816866547
#Sta/Elev= 30
       0 1897.84     7.5 1897.12    27.1 1893.81    43.6 1890.22    56.7 1885.82
    89.5 1870.25   102.6 1865.48   109.4 1863.74   121.8 1861.16   135.4 1859.65
   174.8 1859.55   178.1 1857.49  180.841854.978   184.7 1852.96   194.5 1851.77
   201.1 1852.54  207.991854.685   214.2 1856.34   230.6  1858.1   233.9 1859.14
   237.1 1860.93   250.3 1869.91   256.9 1876.45   260.1 1881.01   263.4  1884.4
   276.6 1895.59   280.7  1897.4   296.2 1901.47   319.2 1909.08   341.2 1918.54
#Mann= 5 ,-1 , 0
       0     .06       0   49.97      .1       0  180.84    .045       0
  207.99      .1       0  250.01      .1       0
Bank Sta=180.84,207.99
XS Rating Curve= 0 ,0
Exp/Cntr=0.3,0.1

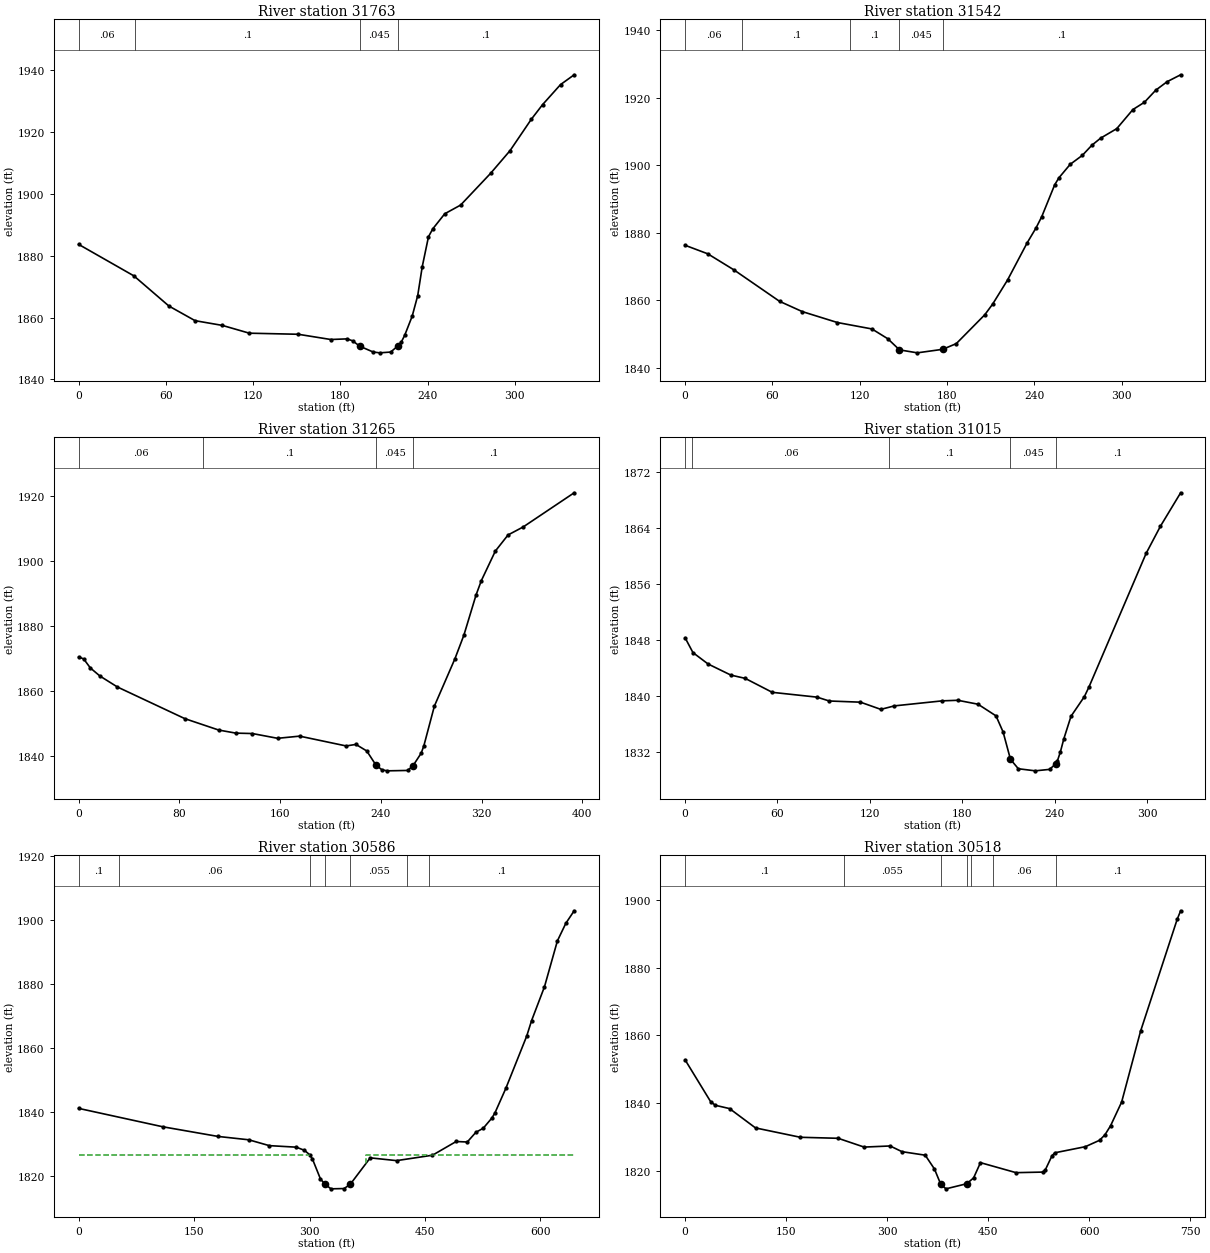
Type RM Length L Ch R = 1 ,31763   ,217.6,220.8,219.4
XS GIS Cut Line= 2
 2070049.4166767310836.8274772172069749.93761685310674.066975966
#Sta/Elev= 30
       0 1883.65      38 1873.47    62.1 1863.72    80.1 1858.99    98.8 1857.47
   117.4 1854.95     151  1854.6   173.4 1852.91   184.6 1853.11   188.4 1852.49
  193.371850.735   202.5 1848.88     207  1848.6   214.6 1848.85  219.591850.854
     222 1852.18   224.2 1854.21   229.4 1860.45   233.2  1867.1   236.3 1876.41
   240.6 1886.11   243.6 1888.69   251.8 1893.54   262.7 1896.35   283.3 1906.59
   296.7 1913.94   311.3 1924.06   319.1 1928.82   331.4 1935.27   340.8 1938.45
#Mann= 4 ,-1 , 0
       0     .06       0   38.84      .1       0  193.37    .045       0
  219.59      .1       0
Bank Sta=193.37,219.59
XS Rating Curve= 0 ,0
Exp/Cntr=0.3,0.1

Type RM Length L Ch R = 1 ,31542   ,272.3,276.9,282.2
XS GIS Cut Line= 2
 2070167.9062691310687.0879472942069882.75001526310500.889828876
#Sta/Elev= 30
       0 1876.29    15.6 1873.76    33.6 1868.99    64.9 1859.69    80.6 1856.63
   104.7  1853.4   128.4  1851.5   139.3  1848.6  147.36  1845.3   159.6 1844.42
  177.041845.463   186.4 1847.15     206 1855.71   211.4 1858.87   221.6 1865.98
   235.1    1877   241.2 1881.43   245.1 1884.73     254 1894.18   256.9 1896.26
   264.7 1900.28     273 1902.92   279.6 1905.94   285.6 1908.03   296.7 1910.85
   307.8 1916.51   315.7 1918.66   323.5 1922.25   331.3 1924.76   340.6 1926.81
#Mann= 5 ,-1 , 0
       0     .06       0   39.39      .1       0  113.57      .1       0
  147.36    .045       0  177.04      .1       0
Bank Sta=147.36,177.04
XS Rating Curve= 0 ,0
Exp/Cntr=0.3,0.1

Type RM Length L Ch R = 1 ,31265   ,250.5,250.1,248.3
XS GIS Cut Line= 2
2070342.38525087310573.8066777892070101.49990585310262.608481288
#Sta/Elev= 30
       0 1870.53       4 1869.92     9.3 1867.14    16.9 1864.65    30.8 1861.27
    84.4 1851.51   111.2 1848.01   124.8 1847.06     138 1846.93     158 1845.46
   175.5 1846.13   212.4 1843.11   220.2 1843.58   228.8 1841.56  236.121837.192
   240.9 1835.75   245.1 1835.44   261.3 1835.56  265.641837.084     272 1840.87
   274.1  1843.1   282.5 1855.39   298.8 1869.96   305.9 1877.21   315.6 1889.63
   319.8 1894.05   330.9 1903.14     341 1908.11     353 1910.57   393.5  1921.1
#Mann= 4 ,-1 , 0
       0     .06       0   98.86      .1       0  236.12    .045       0
  265.64      .1       0
Bank Sta=236.12,265.64
XS Rating Curve= 0 ,0
Exp/Cntr=0.3,0.1

Type RM Length L Ch R = 1 ,31015   ,411,429,439.9
XS GIS Cut Line= 2
2070553.32282111310418.8584968752070338.47909069310179.275314629
#Sta/Elev= 30
       0 1848.31     5.1 1846.19    14.9 1844.56    29.7 1842.97      39  1842.5
    56.6  1840.5    85.7 1839.81    93.6 1839.26   113.9 1839.09   127.1 1838.06
   135.9 1838.56     167 1839.28   177.1 1839.36   190.2  1838.8   201.9 1837.13
   206.5 1834.83  211.291830.909   216.4 1829.56   227.4 1829.26   236.7 1829.47
  240.541830.237   241.7 1830.64   243.7 1831.96   245.9 1833.81   250.6 1837.07
   259.3 1839.89   262.3 1841.28   299.4  1860.4   308.7 1864.29   321.8 1869.07
#Mann= 5 ,-1 , 0
       0      .1       0    4.48     .06       0   132.5      .1       0
  211.29    .045       0  240.54      .1       0
Bank Sta=211.29,240.54
XS Rating Curve= 0 ,0
Exp/Cntr=0.5,0.3

Type RM Length L Ch R = 1 ,30586   ,76.3,68.5,80.9
XS GIS Cut Line= 5
2070632.74982759310326.4108471272070742.12493694 310036.04627037
2070759.05206844309976.1503928012070765.56255412309948.806615457
2070622.33318177309752.191851214
#Sta/Elev= 30
       0 1841.23   109.4 1835.49   181.1 1832.48   221.1 1831.43   247.7 1829.61
   282.8 1829.13   293.3 1828.16   300.3 1826.76   303.8 1825.44   314.2 1819.23
  320.111817.561   327.9 1816.13   344.9 1816.22  352.871817.518   378.9  1825.8
   413.1 1824.93   459.8 1826.62   490.6  1830.9     505 1830.74   516.1 1833.75
   525.8 1835.05   536.9  1838.2     541 1839.85   555.1 1847.48   582.2 1863.77
   588.6 1868.64   605.3 1879.16   622.1 1893.49   633.1 1898.99   643.9 1902.88
#Mann= 7 ,-1 , 0
       0      .1       0   52.35     .06       0  300.48    .055       0
  320.11    .045       0  352.87    .055       0  427.27     .06       0
  455.55      .1       0
#XS Ineff= 2 ,-1
       0  300.11  1826.8  372.87  643.88  1826.8
Permanent Ineff=
       F       F
Bank Sta=320.11,352.87
XS Rating Curve= 0 ,0
Exp/Cntr=0.5,0.3

Type RM Length L Ch R = 1 ,30518   ,194.5,185.3,154.7
XS GIS Cut Line= 4
2070679.62506193310343.3376505372070799.41648903310024.327461794
 2070828.0624291309925.3689982892070650.97912186 309693.59813638
#Sta/Elev= 30
       0 1852.78    37.9 1840.46    44.9 1839.38      66 1838.41   104.5 1832.71
   171.1 1829.95   227.2 1829.65   265.7 1827.06   304.3 1827.39   321.9 1825.71
   356.4 1824.67   370.1  1820.6  379.391816.124   387.2 1814.75  418.031816.258
   428.2 1817.97   438.4 1822.47   491.2 1819.52   530.9 1819.69   534.5 1820.28
   544.6 1824.51   548.8 1825.38   594.1 1827.18   615.1 1829.06   623.1 1830.66
   631.5 1833.35   647.9 1840.32     676 1861.21   730.4 1894.23   735.5 1896.73
#Mann= 7 ,-1 , 0
       0      .1       0  235.69    .055       0  379.39    .045       0
  418.03    .055       0  424.87      .1       0  456.53     .06       0
  550.45      .1       0
Bank Sta=379.39,418.03
XS Rating Curve= 0 ,0
Exp/Cntr=0.5,0.3

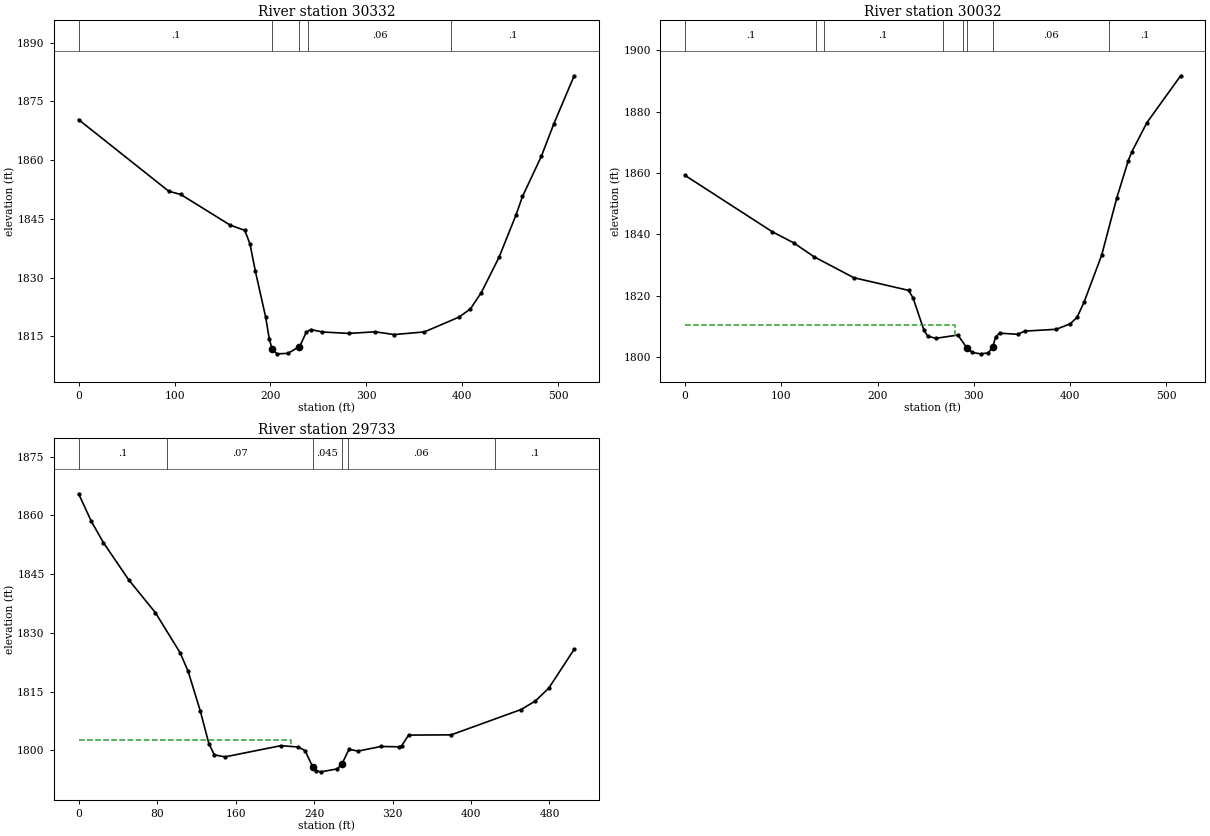
Type RM Length L Ch R = 1 ,30332   ,299.5,300.3,298.4
XS GIS Cut Line= 3
 2071120.5972771309980.0565529612070950.93094978309856.390133634
 2070695.2500307309687.087650716
#Sta/Elev= 30
       0 1870.35      94 1852.05   106.4 1851.24   158.1 1843.38   173.2 1842.06
   178.6  1838.6   184.3 1831.56     195 1819.86   198.7 1814.36  201.711811.723
   206.7  1810.5   218.3 1810.62  229.531812.286   230.5 1812.39   237.5 1816.12
   242.1 1816.71   253.9 1816.09   281.7 1815.72   309.2 1816.13   328.9 1815.43
   360.4  1816.1   396.6 1819.89   408.4 1821.98   419.8 1826.16   438.2 1835.14
     456 1846.02   462.7 1850.71   482.4 1860.99   495.5 1869.35   516.6 1881.56
#Mann= 5 ,-1 , 0
       0      .1       0  201.71    .045       0  229.53      .1       0
  239.49     .06       0  388.27      .1       0
Bank Sta=201.71,229.53
XS Rating Curve= 0 ,0
Exp/Cntr=0.3,0.1

Type RM Length L Ch R = 1 ,30032   ,295.3,298.8,304.6
XS GIS Cut Line= 3
2071291.60415295309743.5114223812071038.63385835309576.088856965
2070861.91669211309459.657331288
#Sta/Elev= 30
       0 1859.24    90.7 1840.85   112.9 1837.24     134 1832.71   175.3 1825.88
   232.2 1821.75   236.9  1819.3   248.1 1808.87   252.1 1806.81   260.6 1806.11
   283.5 1807.17  292.681803.047   298.4 1801.48   307.1 1801.04     315 1801.34
  319.63 1803.17   322.8 1806.61   326.8 1807.78   345.8 1807.42   352.9 1808.45
   385.7 1809.05   400.3 1810.85   407.4 1812.98   414.5 1817.81   432.9  1833.2
   448.6 1851.86   460.4 1863.89   464.2 1866.91     480 1876.49     515 1891.75
#Mann= 8 ,-1 , 0
       0      .1       0  135.64      .1       0  143.85      .1       0
  267.83      .1       0  288.57     .06       0  292.68    .045       0
  319.63     .06       0  441.05      .1       0
#XS Ineff= 2 , 0
          280.14 1810.55
Permanent Ineff=
       F       F
Bank Sta=292.68,319.63
XS Rating Curve= 0 ,0
Exp/Cntr=0.3,0.1

Type RM Length L Ch R = 1 ,29733   ,299.5,296.8,289.7
XS GIS Cut Line= 3
2071420.51039118309589.865404218 2071270.9178426309391.202087626
2071118.42700586309184.917723298
#Sta/Elev= 30
       0  1865.5    12.9 1858.49    25.3 1853.02      51 1843.56    78.3 1835.15
   103.4 1824.95   111.6 1820.21   123.9 1810.18   132.8 1801.72   138.3 1798.87
   149.2 1798.35     206  1801.2   223.8 1800.88   230.8 1799.96  238.68 1795.78
   241.9  1794.8   247.1 1794.53   263.4 1795.27  268.171796.425   275.7 1800.29
   284.8 1799.82   308.1    1801     327 1800.92   329.3 1801.18   336.4 1803.91
   379.8 1803.97   451.1 1810.44   465.4 1812.57   479.2 1815.85   505.2 1825.81
#Mann= 6 ,-1 , 0
       0      .1       0   90.19     .07       0  238.68    .045       0
  268.17     .07       0  274.54     .06       0  424.21      .1       0
#XS Ineff= 2 , 0
          216.98 1802.56
Permanent Ineff=
       F       F
Bank Sta=238.68,268.17
XS Rating Curve= 0 ,0
Exp/Cntr=0.3,0.1