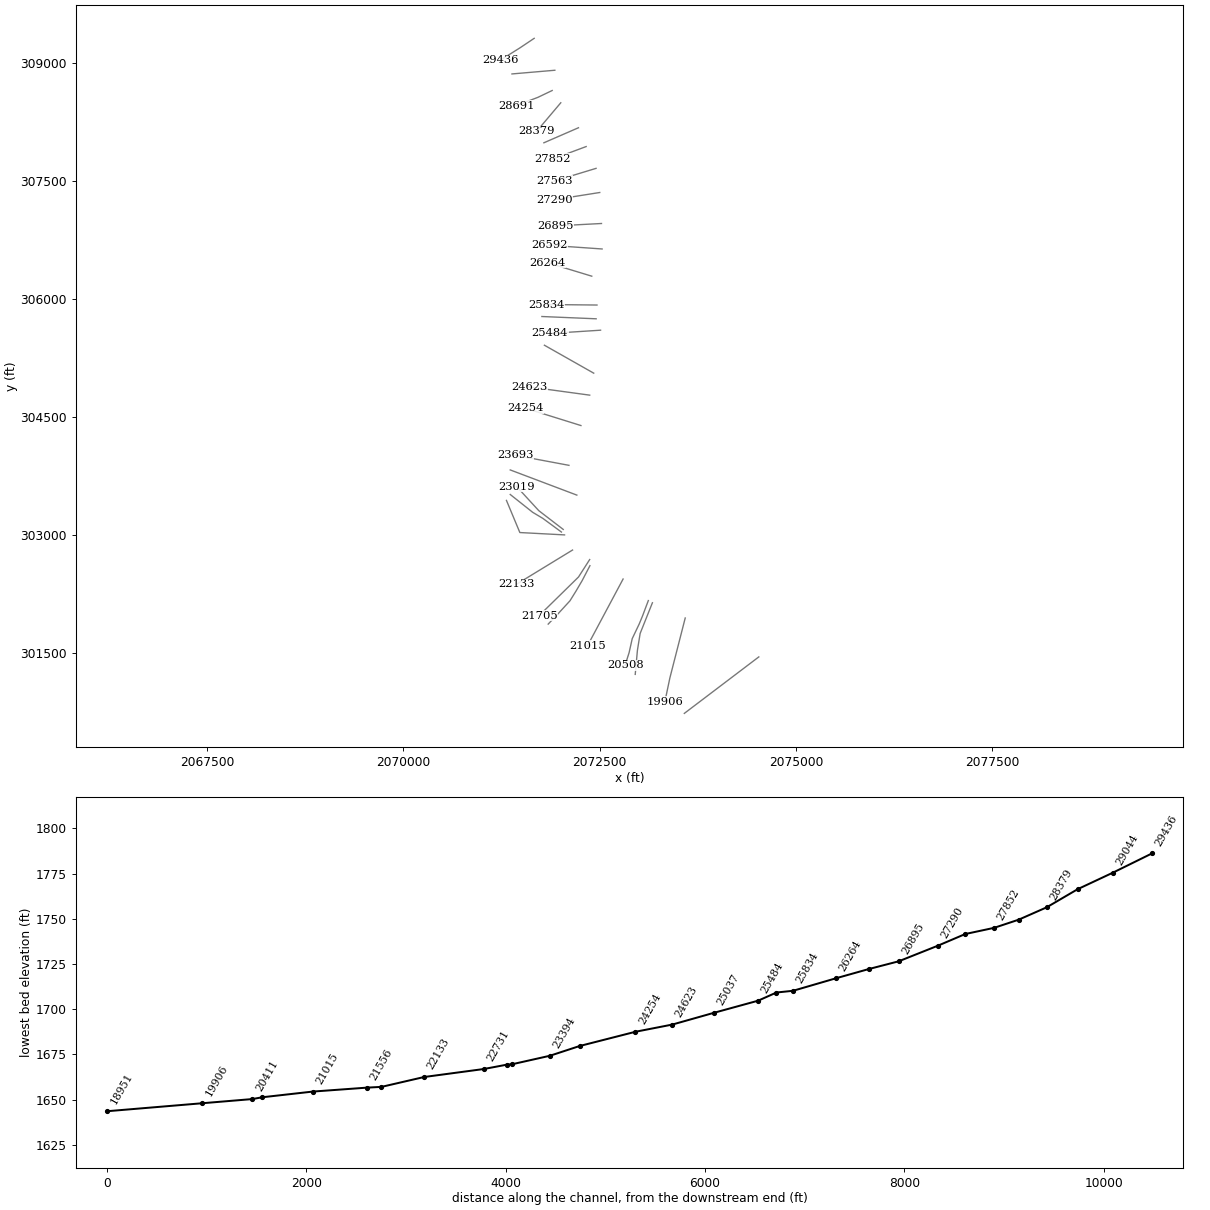
HEC-RAS study KTCHNCK.prj: KTCHNCK

--- KTCHNCK.g01 (geometry) --- (continued)

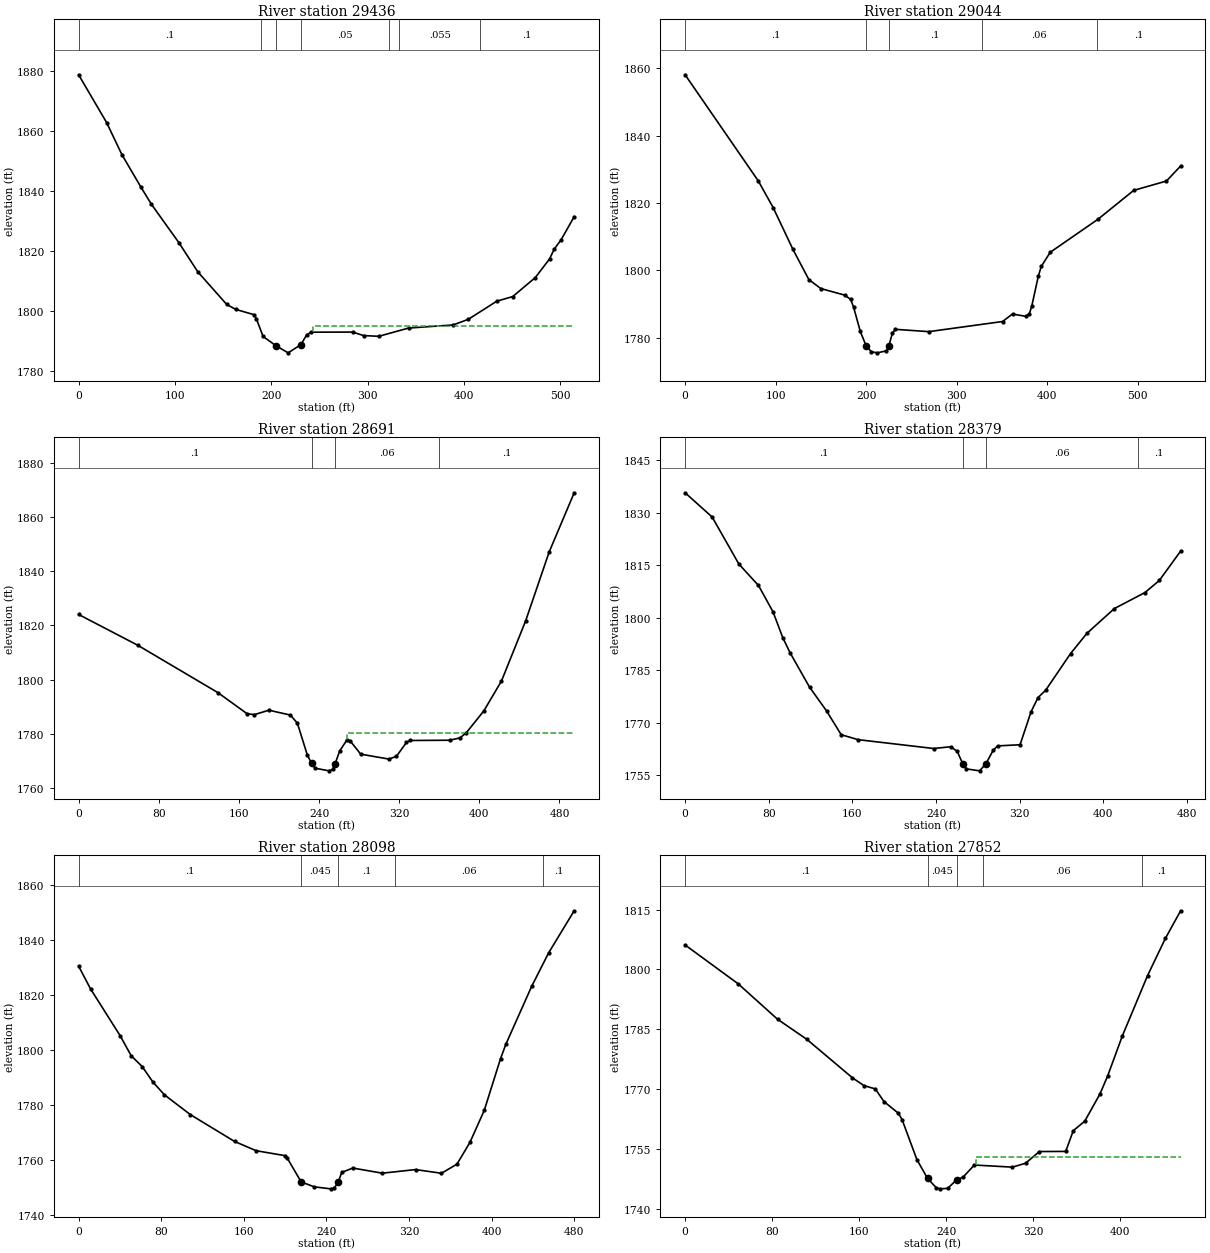
Type RM Length L Ch R = 1 ,29436   ,398.9,392.6,386.6
XS GIS Cut Line= 3
 2071666.6040591309319.0322844682071485.73499829309197.919009626
2071234.31260085309040.386516288
#Sta/Elev= 30
       0 1878.71    29.1 1862.77    44.9 1852.13    64.6 1841.35    75.6 1835.57
     104 1822.85   123.8 1813.07   153.7 1802.26   163.1  1800.6   182.1 1798.84
   184.4 1797.57   191.5 1791.59  204.681788.535   217.5 1786.14  230.721788.876
   236.6 1792.05   241.3 1793.02   284.4 1793.05   295.8 1791.89   311.5 1791.64
   342.5 1794.39   388.8 1795.43   404.4 1797.28   434.1 1803.34   450.6 1804.87
   474.1 1811.21   488.9 1817.43   493.6 1820.63   500.8 1823.76   514.4 1831.47
#Mann= 7 ,-1 , 0
       0      .1       0  189.15     .05       0  204.68    .045       0
  230.72     .05       0  322.11     .06       0  332.64    .055       0
  416.59      .1       0
#XS Ineff= 1 ,-1
  243.46  514.37  1795.2
Permanent Ineff=
       F
Bank Sta=204.68,230.72
XS Rating Curve= 0 ,0
Exp/Cntr=0.3,0.1

Type RM Length L Ch R = 1 ,29044   ,346.6,352.9,353.1
XS GIS Cut Line= 2
2071929.62485853308912.7821127182071384.05213079308865.907206461
#Sta/Elev= 30
       0 1858.13    80.8 1826.62    97.3 1818.66   119.2 1806.22   136.8 1797.25
   149.9  1794.6   176.3 1792.65   182.9 1791.38   186.2 1789.07   193.6 1781.84
  200.021777.604   205.9  1775.8   212.5 1775.49   222.4 1776.09     2251777.422
     229 1781.27   232.3 1782.48   269.3 1781.79   350.8  1784.8   361.8 1787.03
   377.2  1786.3   380.4 1787.08   383.1 1789.39   390.3 1798.25   393.6 1801.18
   403.5 1805.38   456.2 1815.18   495.7 1823.77   531.9 1826.55   547.6 1831.02
#Mann= 5 ,-1 , 0
       0      .1       0  200.02    .045       0     225      .1       0
  327.97     .06       0  454.93      .1       0
Bank Sta=200.02,225
XS Rating Curve= 0 ,0
Exp/Cntr=0.3,0.1

Type RM Length L Ch R = 1 ,28691   ,305.1,311.4,316.5
XS GIS Cut Line= 3
2071895.77092361308654.9696362172071713.47929344308567.730309382
2071440.04152012308463.563522965
#Sta/Elev= 30
       0 1824.03      59 1812.69     139 1795.22   168.1 1787.45   175.4 1787.09
   189.9 1788.73   211.4 1786.94   218.4 1783.93   228.2 1772.32  232.551769.102
     236 1767.34     250 1766.37   253.5 1766.89  256.091768.996   260.6  1773.7
   267.6 1777.63   271.1 1777.41   281.6 1772.52   309.7 1770.71   317.2 1771.69
   327.3 1776.85   330.8 1777.56   370.6 1777.66   380.7 1778.53     387  1780.4
   404.5 1788.47   422.1 1799.47   446.2 1821.62   469.7 1847.04   494.7 1868.91
#Mann= 4 ,-1 , 0
       0      .1       0  232.55    .045       0  256.09     .06       0
  360.15      .1       0
#XS Ineff= 2 , 0
                          268.25         1780.35
Permanent Ineff=
       F       F
Bank Sta=232.55,256.09
XS Rating Curve= 0 ,0
Exp/Cntr=0.3,0.1

Type RM Length L Ch R = 1 ,28379   ,289.6,281.1,274.5
XS GIS Cut Line= 2
2072005.14570487 308498.719620632071699.15615937308136.740685791
#Sta/Elev= 30
       0 1835.76    25.9 1828.83    51.5 1815.37    70.2 1809.28    84.1 1801.75
    93.4 1794.39   100.4 1790.06     119 1780.25   135.3 1773.44   149.3 1766.65
   165.4 1765.23   237.8  1762.7   254.1 1763.21   260.3 1761.88  265.571758.346
   268.9 1756.88   281.7 1756.32  287.661758.289   294.6 1762.14   298.9 1763.45
   320.4 1763.77   330.9 1773.18   337.6 1777.25   344.9 1779.35   368.7 1789.82
   384.4 1795.62   410.6 1802.68   439.9 1807.26   453.6  1810.7     474  1819.1
#Mann= 4 ,-1 , 0
       0      .1       0  265.57    .045       0  287.66     .06       0
  433.16      .1       0
Bank Sta=265.57,287.66
XS Rating Curve= 0 ,0
Exp/Cntr=0.3,0.1

Type RM Length L Ch R = 1 ,28098   ,247.2,246.2,245.5
XS GIS Cut Line= 2
2072230.40608111308181.0112665442071790.30197445307989.605153292
#Sta/Elev= 30
       0 1830.54    11.5  1822.3    40.1  1805.3    50.9 1797.94    61.6 1793.98
    71.9 1788.39    83.1 1783.71   108.1 1776.54     151 1766.74   171.9 1763.37
   199.4  1761.6   201.9 1760.76  215.481752.025   228.2 1750.21     244 1749.49
   247.6 1749.74  251.391751.958   254.8 1755.46   265.5 1757.06   294.1 1755.19
   326.3  1756.5   351.4 1755.16   366.4 1758.48   378.9 1766.36   392.8 1778.03
   408.6 1796.89   413.8 1802.17   438.7 1823.18   455.1 1835.34   479.9 1850.71
#Mann= 5 ,-1 , 0
       0      .1       0  215.48    .045       0  251.39      .1       0
  306.79     .06       0  449.32      .1       0
Bank Sta=215.48,251.39
XS Rating Curve= 0 ,0
Exp/Cntr=0.3,0.1

Type RM Length L Ch R = 1 ,27852   ,290.8,289.6,288.5
XS GIS Cut Line= 2
2072328.06238186307941.4280842992071900.97924653307782.573743209
#Sta/Elev= 30
       0 1806.12    48.9 1796.36      85  1787.5   111.9 1782.47   153.9 1772.81
   164.4 1770.87   174.9 1770.03   182.9 1766.86     196 1763.96   199.5 1762.36
   213.2 1752.29  222.921747.615     231 1745.26   234.5 1744.98   241.5  1745.1
  249.851747.291   255.5 1747.88     266 1750.95     301 1750.42   313.1  1751.4
   325.8 1754.33     350 1754.36     357 1759.57   367.5 1761.93   381.5 1768.76
   388.5 1773.22     402 1783.26   425.3 1798.45   441.7 1807.79   455.7 1814.69
#Mann= 5 ,-1 , 0
       0      .1       0  222.92    .045       0  249.85     .05       0
  273.64     .06       0  420.38      .1       0
#XS Ineff= 1 ,-1
  267.12  455.67 1752.86
Permanent Ineff=
       F
Bank Sta=222.92,249.85
XS Rating Curve= 0 ,0
Exp/Cntr=0.3,0.1

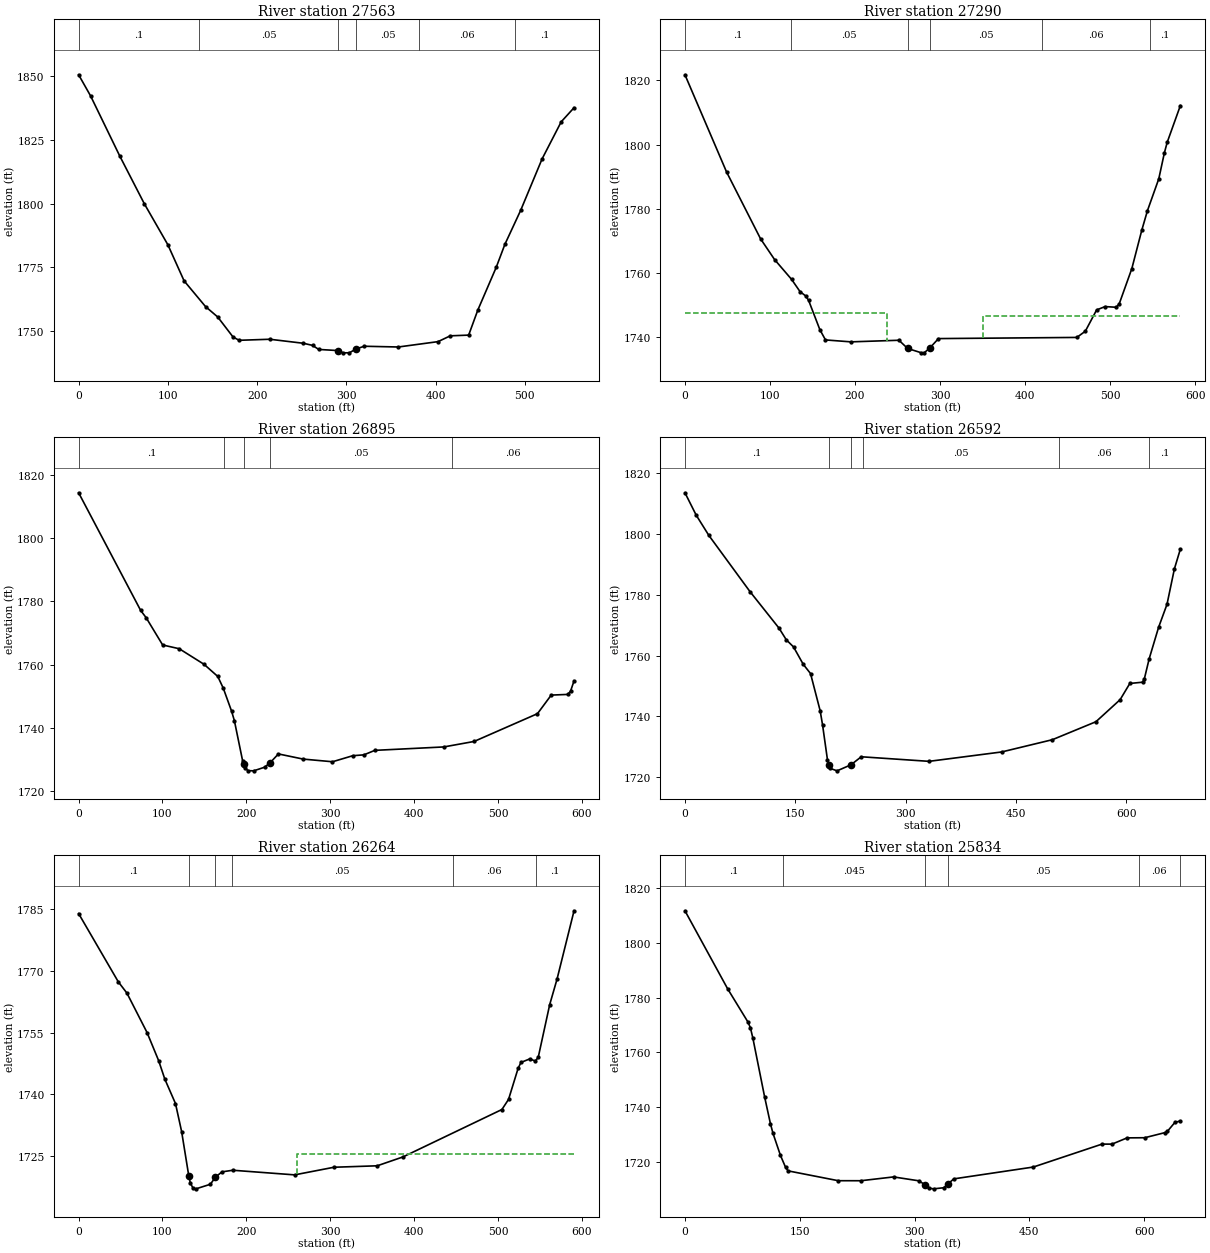
Type RM Length L Ch R = 1 ,27563   ,274.2,272.8,271
XS GIS Cut Line= 2
2072454.36462268307664.0844788852071923.11470094307502.626140371
#Sta/Elev= 30
       0 1850.43    13.4 1842.16    46.2 1818.55    73.6 1799.95     100 1783.88
   118.2 1769.74   142.2 1759.68   155.9 1755.59   173.1 1747.74   179.9 1746.47
   214.2 1746.88     252  1745.3   262.1 1744.48   269.1 1742.89  290.621742.451
   296.5 1741.56   303.4 1741.58  310.651743.019   319.9 1744.14   358.3 1743.85
   402.8 1745.95   416.5 1748.22   437.1  1748.5   447.4 1758.34     468 1775.05
   477.7 1784.04   495.4 1797.36   519.4  1817.5   540.8 1832.01   555.2 1837.54
#Mann= 6 ,-1 , 0
       0      .1       0  135.17     .05       0  290.62    .045       0
  310.65     .05       0  381.73     .06       0  489.38      .1       0
Bank Sta=290.62,310.65
XS Rating Curve= 0 ,0
Exp/Cntr=0.3,0.1

Type RM Length L Ch R = 1 ,27290   ,395,395.3,390.9
XS GIS Cut Line= 2
2072501.23952895307356.7927706242071925.71869835 307265.64695555
#Sta/Elev= 30
       0 1821.76      49 1791.45    88.9 1770.68   105.5 1764.17   125.4 1758.04
   135.4  1754.2     142 1752.88   145.4 1751.51   158.7 1742.35   165.3 1739.17
   195.2 1738.57   251.7 1739.07  261.881736.517   278.2 1735.15   281.6 1735.21
  288.071736.692   298.2 1739.59   460.9 1739.95   470.9 1741.88   484.2 1748.52
   494.2 1749.56   507.4 1749.34   510.8 1750.43   525.6 1761.38   537.3 1773.34
     544 1779.46   557.3 1789.35   563.9 1797.45   567.2 1800.72   582.7 1812.17
#Mann= 6 ,-1 , 0
       0      .1       0   124.6     .05       0  261.88    .045       0
  288.07     .05       0   419.9     .06       0  547.03      .1       0
#XS Ineff= 2 ,-1
       0  238.03 1747.44  350.08  582.69 1746.53
Permanent Ineff=
       F       F
Bank Sta=261.88,288.07
XS Rating Curve= 0 ,0
Exp/Cntr=0.3,0.1

Type RM Length L Ch R = 1 ,26895   ,303.8,302.8,299.8
XS GIS Cut Line= 2
2072523.37498337306962.2614074652071933.53134677 306931.01146996
#Sta/Elev= 30
       0 1814.31      74 1777.13    80.5 1774.85   100.2 1766.23     120 1765.04
   149.5 1760.13   165.9 1756.29   172.5 1752.56   182.4  1745.3   185.7 1742.33
   195.5 1729.68  196.821728.708   198.8 1727.22   202.1 1726.53   208.7 1726.47
   221.8 1727.62  228.441729.063   238.2 1731.81   267.8 1730.18   302.7 1729.34
   326.9 1731.25   340.1 1731.52   353.2 1732.94   435.4 1734.02   471.5 1735.75
   547.1 1744.53   563.5  1750.4   583.2 1750.61   586.5 1751.61   590.7  1754.9
#Mann= 5 ,-1 , 0
       0      .1       0  173.45     .05       0  196.82    .045       0
  228.44     .05       0  445.35     .06       0
Bank Sta=196.82,228.44
XS Rating Curve= 0 ,0
Exp/Cntr=0.3,0.1

Type RM Length L Ch R = 1 ,26592   ,330.1,327.6,323.1
XS GIS Cut Line= 2
2072531.18763179306638.042567715 2071859.3123351306684.917802051
#Sta/Elev= 30
       0 1813.48    15.3 1806.12    32.5 1799.47    88.4 1781.02   127.9 1769.01
   137.8 1765.18   147.6 1762.85   160.8 1757.14   170.7 1754.11   183.8 1741.89
   187.1 1737.18   193.7 1725.83   195.91723.973     197    1723   206.8 1722.15
  225.591724.122   239.7 1726.77   331.8 1725.27   430.5 1728.35   499.4 1732.37
   558.7 1738.28   591.6 1745.53   604.8 1750.85   622.4 1751.27   624.5 1752.34
   631.1 1758.97   643.9  1769.3   655.3 1776.83   665.4 1788.51   673.5 1794.99
#Mann= 6 ,-1 , 0
       0      .1       0   195.9    .045       0  225.59      .1       0
  242.02     .05       0  507.88     .06       0  631.02      .1       0
Bank Sta=195.9,225.59
XS Rating Curve= 0 ,0
Exp/Cntr=0.3,0.1

Type RM Length L Ch R = 1 ,26264   ,426.2,430.3,434.5
XS GIS Cut Line= 2
2072399.67706802306291.6886016282071834.57288328306463.563585967
#Sta/Elev= 30
       0 1783.86    47.3  1767.3    57.6 1764.56    81.6 1754.99    95.4 1748.18
   102.8 1743.68   115.5 1737.76   122.8 1730.98  131.431720.098   133.1 1718.53
   136.5 1717.19   139.9 1717.07   157.1 1718.18  163.171719.914   170.9 1721.19
   183.9 1721.58   257.5 1720.46   304.5 1722.31     356 1722.66   386.8 1724.82
   504.7 1736.32   512.6 1738.77     524  1746.3   527.4 1747.74   537.7 1748.58
   544.6  1748.1     548 1748.98   561.7 1761.79   570.4 1767.94   590.7 1784.54
#Mann= 6 ,-1 , 0
       0      .1       0  131.43    .045       0  163.17      .1       0
  182.44     .05       0  445.82     .06       0  544.85      .1       0
#XS Ineff= 1 ,-1
   260.1  590.66 1725.48
Permanent Ineff=
       F
Bank Sta=131.43,163.17
XS Rating Curve= 0 ,0
Exp/Cntr=0.3,0.1

Type RM Length L Ch R = 1 ,25834   ,166,165.3,164.6
XS GIS Cut Line= 2
2072466.08343127305924.5010157972071818.94791451305931.011501461
#Sta/Elev= 30
       0 1811.69    55.9 1783.13    82.2 1771.11    85.5 1768.98    88.7 1765.21
   104.2 1743.55   111.7 1733.91     115 1730.43   124.8 1722.34   131.4 1718.04
   134.7 1716.72   200.3 1713.13   229.8 1713.12   272.5 1714.51   305.6 1713.09
  313.781711.608   318.4 1710.41   324.8 1710.16   338.1 1710.56  343.191711.853
   351.2  1713.8   455.1 1718.12   544.8 1726.49   557.9 1726.49   577.6 1728.77
   600.6 1728.82   626.8 1730.67   630.1 1731.11     640  1734.4   647.2 1734.95
#Mann= 6 ,-1 , 0
       0      .1       0  128.17    .045       0  313.78    .045       0
  343.19     .05       0   593.1     .06       0  646.14      .1       0
Bank Sta=313.78,343.19
XS Rating Curve= 0 ,0
Exp/Cntr=0.3,0.1

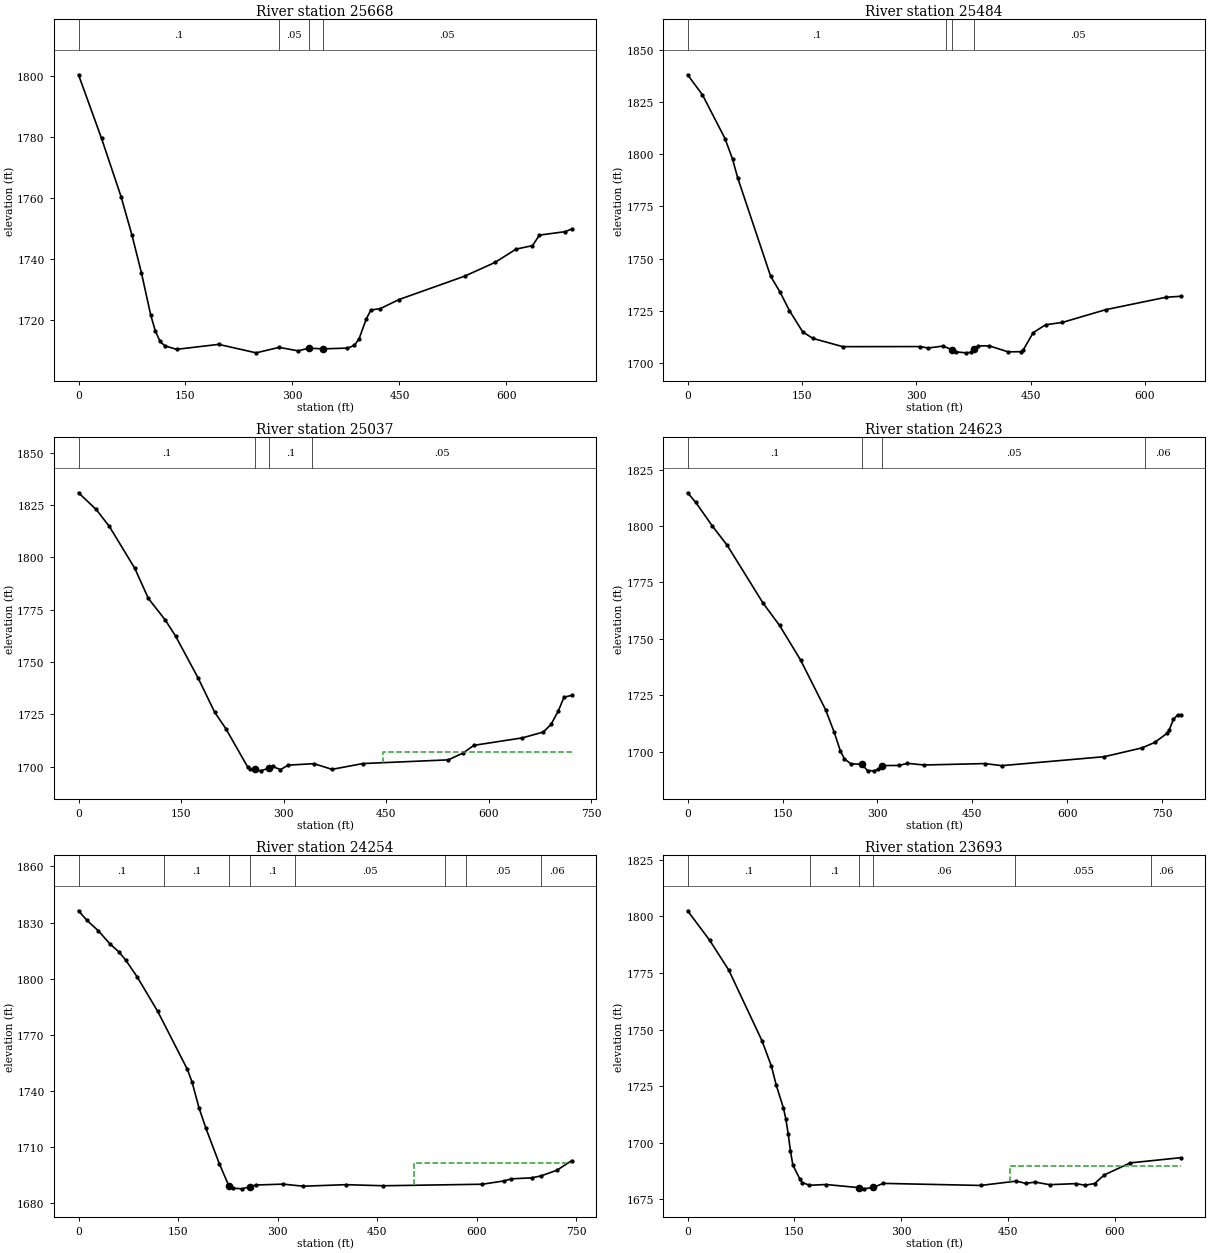
Type RM Length L Ch R = 1 ,25668   ,184.7,184.8,185.7
XS GIS Cut Line= 2
2072455.52107394305749.2531295192071764.72178216305778.330140525
#Sta/Elev= 30
       0 1800.49    32.3  1779.6    59.6 1760.53      75  1747.8    88.1 1735.59
   101.2 1721.67   107.5 1716.53   114.3 1712.98   120.9 1711.55   137.4 1710.37
   196.5    1712     249 1709.22   281.3 1711.01   308.1 1709.87   322.81710.763
   342.81710.524   377.1 1710.78   386.9 1711.67   393.5 1713.92   403.3 1720.25
   409.9 1723.29   422.9 1723.71   449.3 1726.71   541.3 1734.38   583.9 1738.89
   613.5 1743.26   636.5 1744.42   646.3 1747.87   682.5    1749   691.4 1749.87
#Mann= 4 ,-1 , 0
       0      .1       0   281.3     .05       0   322.8    .045       0
   342.8     .05       0
Bank Sta=322.8,342.8
XS Rating Curve= 0 ,0
Exp/Cntr(USF)=0,0
Exp/Cntr=0.3,0.1

Type RM Length L Ch R = 1 ,25484   ,450.9,447,440.6
XS GIS Cut Line= 2
2072511.65617478305604.1883362082071865.82282078305562.521752879
#Sta/Elev= 30
       0 1838.24    19.5 1828.59    49.1 1807.58      59 1797.71    65.6 1788.87
   108.9 1741.51   121.3 1733.88   133.6 1724.99     151 1714.78   164.5 1711.61
   203.6 1707.66   305.6  1707.7   315.4    1707   335.1 1707.93  346.471706.292
   351.6 1705.21   364.7 1704.69   371.3 1704.88  375.891706.378   380.7 1708.01
   396.1 1708.03   420.6 1705.16   437.1 1705.24   440.3 1705.96   453.5 1714.38
   469.9 1718.18   491.9 1719.31   548.8 1725.43   627.7 1731.38   647.2 1731.86
#Mann= 4 ,-1 , 0
       0      .1       0  338.74     .05       0  346.47    .045       0
  375.89     .05       0
Bank Sta=346.47,375.89
XS Rating Curve= 0 ,0
Exp/Cntr=0.3,0.1

Type RM Length L Ch R = 1 ,25037   ,407.4,413.5,417.2
XS GIS Cut Line= 2
2072424.41651985305057.3134457172071796.81246009305412.782222956
#Sta/Elev= 30
       0  1830.9    25.8 1822.93      45 1814.87    82.3 1794.78   102.2 1780.36
   126.9 1770.06   142.2 1762.24   174.8 1742.41   199.1 1726.01   215.4 1718.13
   247.2 1699.91   250.2 1698.79   258.21698.576   266.5 1697.93  278.28  1699.2
   284.1 1700.01   295.4  1698.5   306.7 1700.66   344.4 1701.36   370.8 1698.64
   416.1 1701.42   540.9 1703.18   563.1 1706.56   578.2 1710.12   649.2 1713.69
     680 1716.51   691.3 1720.22   701.4 1726.32   710.2 1733.17   721.3    1734
#Mann= 4 ,-1 , 0
       0      .1       0   258.2    .045       0  278.28      .1       0
  341.74     .05       0
#XS Ineff= 1 ,-1
  445.95  721.28 1706.93
Permanent Ineff=
       F
Bank Sta=258.2,278.28
XS Rating Curve= 0 ,0
Exp/Cntr=0.3,0.1

Type RM Length L Ch R = 1 ,24623   ,371.8,369.6,366.8
XS GIS Cut Line= 2
2072373.63545343  304777.36551482071601.49985862304882.834463954
#Sta/Elev= 30
       0 1814.72    12.8 1810.48    39.3  1799.9    62.5 1791.47   118.8    1766
   145.3 1755.92   178.4 1740.66   218.1 1718.54   231.4 1708.77   241.3  1700.4
   247.9 1696.76     258 1694.58  275.051694.415   284.3 1691.62   294.3 1691.49
   300.9 1692.11  307.791693.827     334 1693.88   347.3 1694.81   373.7 1694.08
   469.8 1694.71   496.3 1693.79   658.5 1697.76   718.3 1701.68     738 1704.06
   757.9 1708.17   761.2 1709.71   767.8 1714.38   774.4 1716.24   779.3 1716.35
#Mann= 4 ,-1 , 0
       0      .1       0  275.05    .045       0  307.79     .05       0
  722.98     .06       0
Bank Sta=275.05,307.79
XS Rating Curve= 0 ,0
Exp/Cntr=0.3,0.1

Type RM Length L Ch R = 1 ,24254   ,559.6,560.8,561.8
XS GIS Cut Line= 2
2072261.65634668304390.6468000412071552.02095494304612.001016125
#Sta/Elev= 30
       0 1836.29    12.8 1831.12      30 1825.56    47.2 1818.63      61 1814.23
    71.3 1809.84    88.5 1800.87   119.4 1782.46   164.1 1751.43   171.1 1744.71
   181.5 1731.02     192 1719.97   212.2 1701.03   225.9 1689.69  227.211689.123
   232.8  1687.9   246.5 1687.51   258.71688.687   267.2 1689.56   308.4 1690.03
   338.7 1688.92   402.8 1689.74   459.6 1689.16   608.5 1689.97   641.8 1691.76
   652.1 1692.84     683  1693.4   697.6 1694.46   721.2 1697.48   743.4 1702.58
#Mann= 8 ,-1 , 0
       0      .1       0  129.45      .1       0  227.21    .045       0
   258.7      .1       0  326.33     .05       0  553.06     .06       0
   583.4     .05       0  697.41     .06       0
#XS Ineff= 1 ,-1
  505.26  743.36 1701.31
Permanent Ineff=
       F
Bank Sta=227.21,258.7
XS Rating Curve= 0 ,0
Exp/Cntr=0.3,0.1

Type RM Length L Ch R = 1 ,23693   ,300.7,298.5,294
XS GIS Cut Line= 2
2072109.31249127303884.1363301282071428.32303962304011.740405634
#Sta/Elev= 30
       0 1802.46    31.1 1789.37    57.8 1776.26   104.5 1745.03   117.8 1733.72
   124.5 1725.41   134.5 1715.44   137.9 1710.66   141.3 1703.88   144.5 1696.21
   147.9 1690.12   157.9 1683.81   161.2  1682.4   171.2 1681.19   194.5 1681.53
  241.071680.146     248 1679.62   261.11680.275   274.7 1682.03   411.6 1681.12
   461.7 1683.03     475 1682.05   488.4 1682.59   508.4 1681.46   545.1 1681.91
   558.5 1681.23   571.8 1681.97   585.4 1685.77   621.7 1691.08   692.8 1693.38
#Mann= 6 ,-1 , 0
       0      .1       0  172.49      .1       0  241.07    .045       0
   261.1     .06       0  459.29    .055       0  651.34     .06       0
#XS Ineff= 2 , 0
                           452.8         1689.75
Permanent Ineff=
       F       F
Bank Sta=241.07,261.1
XS Rating Curve= 0 ,0
Exp/Cntr=0.3,0.1

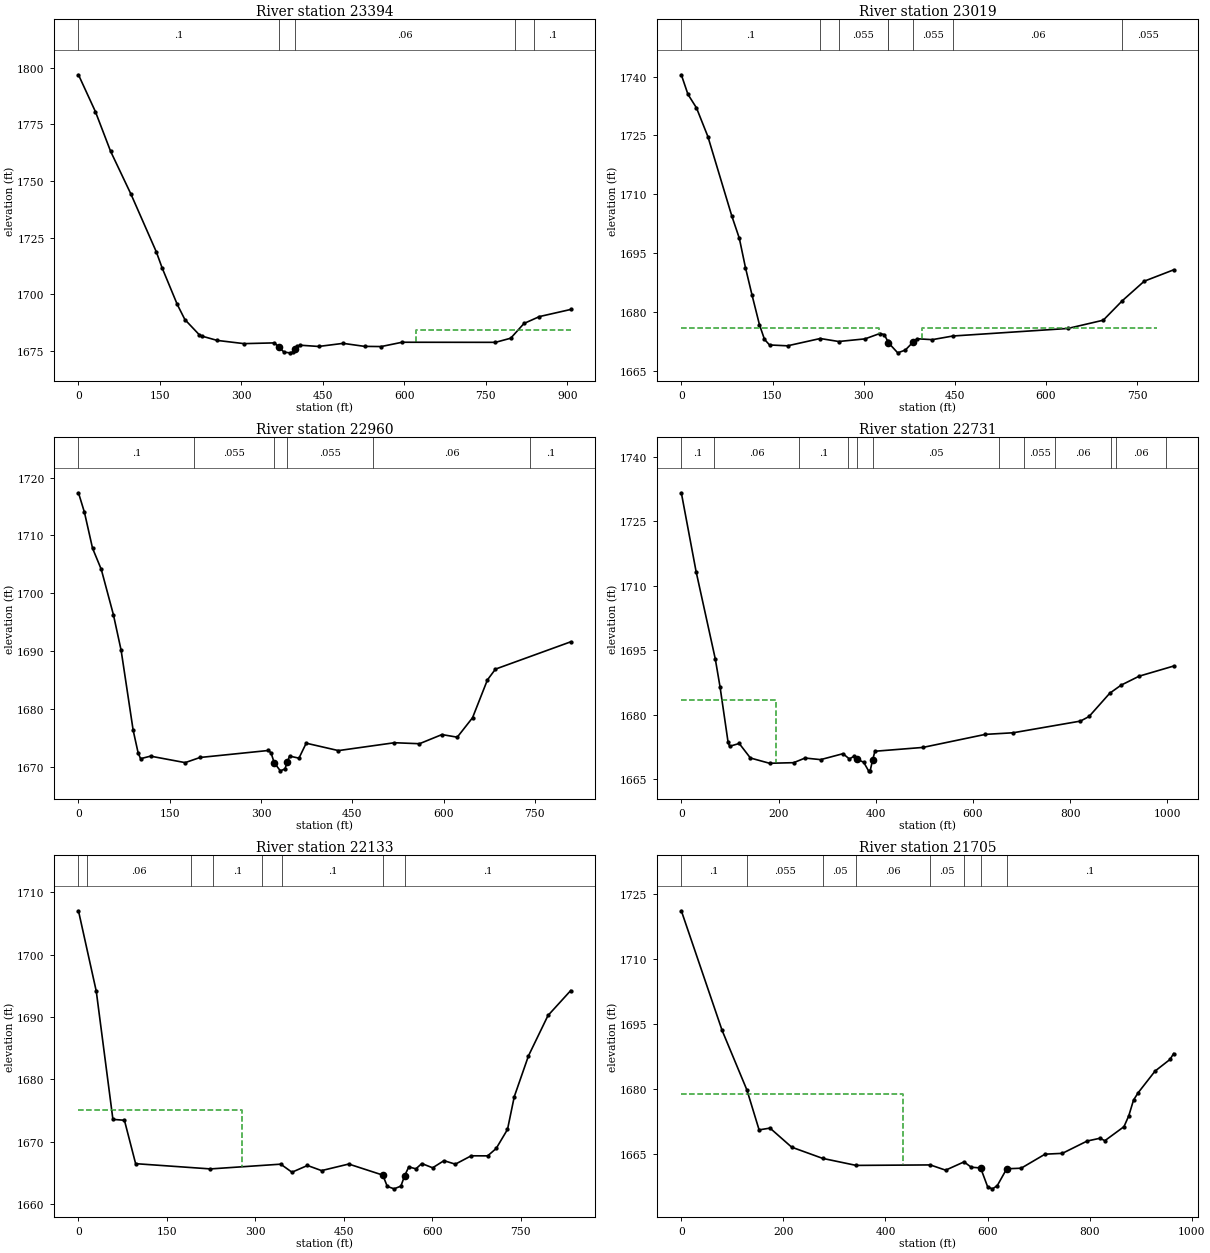
Type RM Length L Ch R = 1 ,23394   ,380.3,374.8,368.1
XS GIS Cut Line= 2
2072209.57278943303505.2302637992071361.91667634303825.542615294
#Sta/Elev= 30
       0 1796.84    31.1 1780.64    59.1 1763.13    96.9 1744.06   143.4 1718.71
   153.8 1711.81   181.9 1695.55   195.9  1688.9   222.2 1682.25   227.3  1681.6
   255.3 1679.71   304.7 1678.29   360.8 1678.62  369.661676.626   378.3 1674.55
   388.8 1674.23   395.3 1674.64   399.11675.752   402.9 1677.04     408  1677.6
   442.1 1677.04   487.2 1678.41   526.7 1677.08   557.2    1677   595.8  1678.9
   767.6 1678.86   795.7 1680.68   820.2 1687.19   848.6 1690.22   906.2 1693.36
#Mann= 5 ,-1 , 0
       0      .1       0  369.66    .045       0   399.1     .06       0
  803.23    .055       0  839.06      .1       0
#XS Ineff= 1 ,-1
  620.83  906.16  1684.1
Permanent Ineff=
       F
Bank Sta=369.66,399.1
XS Rating Curve= 0 ,0
Exp/Cntr=0.5,0.3

Type RM Length L Ch R = 1 ,23019   ,55.1,59.1,64.2
XS GIS Cut Line= 3
2072036.36127364 303068.380186172071725.19777393 303307.31333679
2071442.64584562 303614.60504505
#Sta/Elev= 30
       0 1740.46    10.9 1735.47    24.9 1732.03    43.7 1724.71      83 1704.49
    95.4 1698.79   105.5 1691.31   116.1 1684.45   128.5 1676.77   136.8 1673.02
   145.1  1671.6   174.7 1671.38   228.5 1673.24   258.9 1672.48   302.2 1673.15
   326.4 1674.51   333.8 1674.25   339.5 1672.57   340.8 1672.14     356 1669.59
   368.4 1670.29   380.8 1672.26   387.6 1673.18   412.8 1672.95   446.7 1673.88
   635.8  1675.8   694.1 1677.91   725.5 1682.88   761.5 1687.85   809.8 1690.74
#Mann= 8 ,-1 , 0
       0      .1       0   228.5     .06       0   258.9    .055       0
   339.5    .045       0   340.8    .045       0   380.8    .055       0
   446.7     .06       0   725.5    .055       0
#XS Ineff= 2 ,-1
       0   325.8  1675.8   395.8  783.18  1675.8
Permanent Ineff=
       F       F
Bank Sta=340.8,380.8
XS Rating Curve= 0 ,0
Exp/Cntr=0.5,0.3

Type RM Length L Ch R = 1 ,22960   ,223.7,229.9,233.6
XS GIS Cut Line= 4
2072013.47235336 303034.971885662071776.13980958303209.298209184
2071647.07293019303286.4800451252071361.91667634303513.042584121
#Sta/Elev= 30
       0 1717.37     9.8    1714    23.1 1707.79    37.5 1704.12    57.4  1696.3
    70.1 1690.14    89.9  1676.3    98.1 1672.38   102.1 1671.39   118.4 1671.83
   175.4 1670.71   199.8  1671.6   312.2 1672.81   316.5 1672.41   321.7  1670.7
   331.8 1669.29   339.4 1669.62   343.2 1670.82     347 1671.84   362.4 1671.48
   374.3 1674.07   427.3 1672.79   519.3 1674.15   560.5 1673.98   597.4 1675.56
   622.6 1675.11   647.7 1678.47   672.2 1685.02   685.4 1686.88   809.1  1691.6
#Mann= 6 ,-1 , 0
       0      .1       0  190.68    .055       0   321.7    .045       0
   343.2    .055       0  484.81     .06       0  742.09      .1       0
Bank Sta=321.7,343.2
XS Rating Curve= 0 ,0
Exp/Cntr=0.5,0.3

Type RM Length L Ch R = 1 ,22731   ,578.8,597.4,604.5
XS GIS Cut Line= 3
2072053.32277384302998.7197938712071484.31242895303028.667568624
2071313.73960736303437.521737799
#Sta/Elev= 30
       0 1731.63    30.4 1713.28    69.8 1692.99    79.6 1686.49    96.1 1673.63
    99.3 1672.61   119.1 1673.27   142.1 1669.89   181.5 1668.66   231.1  1668.8
   254.6 1669.88   286.6 1669.51   332.6 1670.89   345.7 1669.67   355.6 1670.31
   362.1 1669.61   375.3 1668.88   385.2  1666.9   388.5 1666.91   393.4 1669.35
   398.3 1671.46   496.9 1672.35   625.6 1675.39   682.5 1675.76   821.1 1678.48
   838.9 1679.55   881.5 1684.97   904.7 1686.84     942 1688.94  1012.8 1691.29
#Mann= 12 ,-1 , 0
       0      .1       0   66.78     .06       0  242.46      .1       0
  342.38     .05       0   362.1    .045       0   393.4     .05       0
  654.41      .1       0  706.01    .055       0  768.79     .06       0
  883.17      .1       0  894.18     .06       0  997.54      .1       0
#XS Ineff= 2 , 0
          195.13  1683.4
Permanent Ineff=
       F       F
Bank Sta=362.1,393.4
XS Rating Curve= 0 ,0
Exp/Cntr=0.3,0.1

Type RM Length L Ch R = 1 ,22133   ,420.6,428.2,432
XS GIS Cut Line= 2
2072154.88556287302806.0115178822071442.64584562302371.115406051
#Sta/Elev= 30
       0 1707.01    30.2 1694.12    58.4 1673.61    77.9 1673.47    96.9 1666.52
   223.7 1665.68   342.9 1666.44   361.9 1665.15   388.2 1666.23   412.1 1665.41
   458.2 1666.46   515.9 1664.69   523.5 1662.88   535.1 1662.49   546.6 1662.93
   552.9 1664.58     560 1666.01     572 1665.69     582 1666.54   600.4 1665.86
   619.6    1667   638.9 1666.44   665.8 1667.78   693.7 1667.77   708.1 1668.95
   727.3    1672   738.8 1677.25   762.9 1683.79     796 1690.25   834.5 1694.24
#Mann= 8 ,-1 , 0
       0      .1       0   14.03     .06       0  190.06     .05       0
  228.59      .1       0  311.31     .05       0  344.77      .1       0
   515.9    .045       0   552.9      .1       0
#XS Ineff= 2 , 0
          277.65 1675.16
Permanent Ineff=
       F       F
Bank Sta=515.9,552.9
XS Rating Curve= 0 ,0
Exp/Cntr=0.3,0.1

Type RM Length L Ch R = 1 ,21705   ,146.3,149.1,148.8
XS GIS Cut Line= 3
2072372.94614074302684.8457529242072231.04907074302463.029643499
2071730.33182373301972.098401316
#Sta/Elev= 30
       0 1721.21    79.9  1693.6   128.7 1679.79   152.4 1670.64   173.8 1671.05
   216.2 1666.65   276.9 1664.06   342.5 1662.44   487.8 1662.55   517.9 1661.34
     554 1663.25     568 1662.02   586.5 1661.85   600.4 1657.45   609.7 1657.03
     619 1657.75   637.6 1661.66   665.9 1661.79   712.7 1665.03   746.6 1665.22
   795.3 1668.07   820.5 1668.71   829.9 1668.14   867.4 1671.38   876.8  1673.9
   886.1 1677.52   895.1  1679.2   928.3 1684.21   957.7 1686.91   964.6 1688.26
#Mann= 8 ,-1 , 0
       0      .1       0   128.7    .055       0   276.9     .05       0
   342.5     .06       0   487.8     .05       0     554     .01       0
   586.5    .045       0   637.6      .1       0
#XS Ineff= 2 , 0
          434.73 1678.94
Permanent Ineff=
       F       F
Bank Sta=586.5,637.6
XS Rating Curve= 0 ,0
Exp/Cntr(USF)=0,0
Exp/Cntr=0.3,0.1

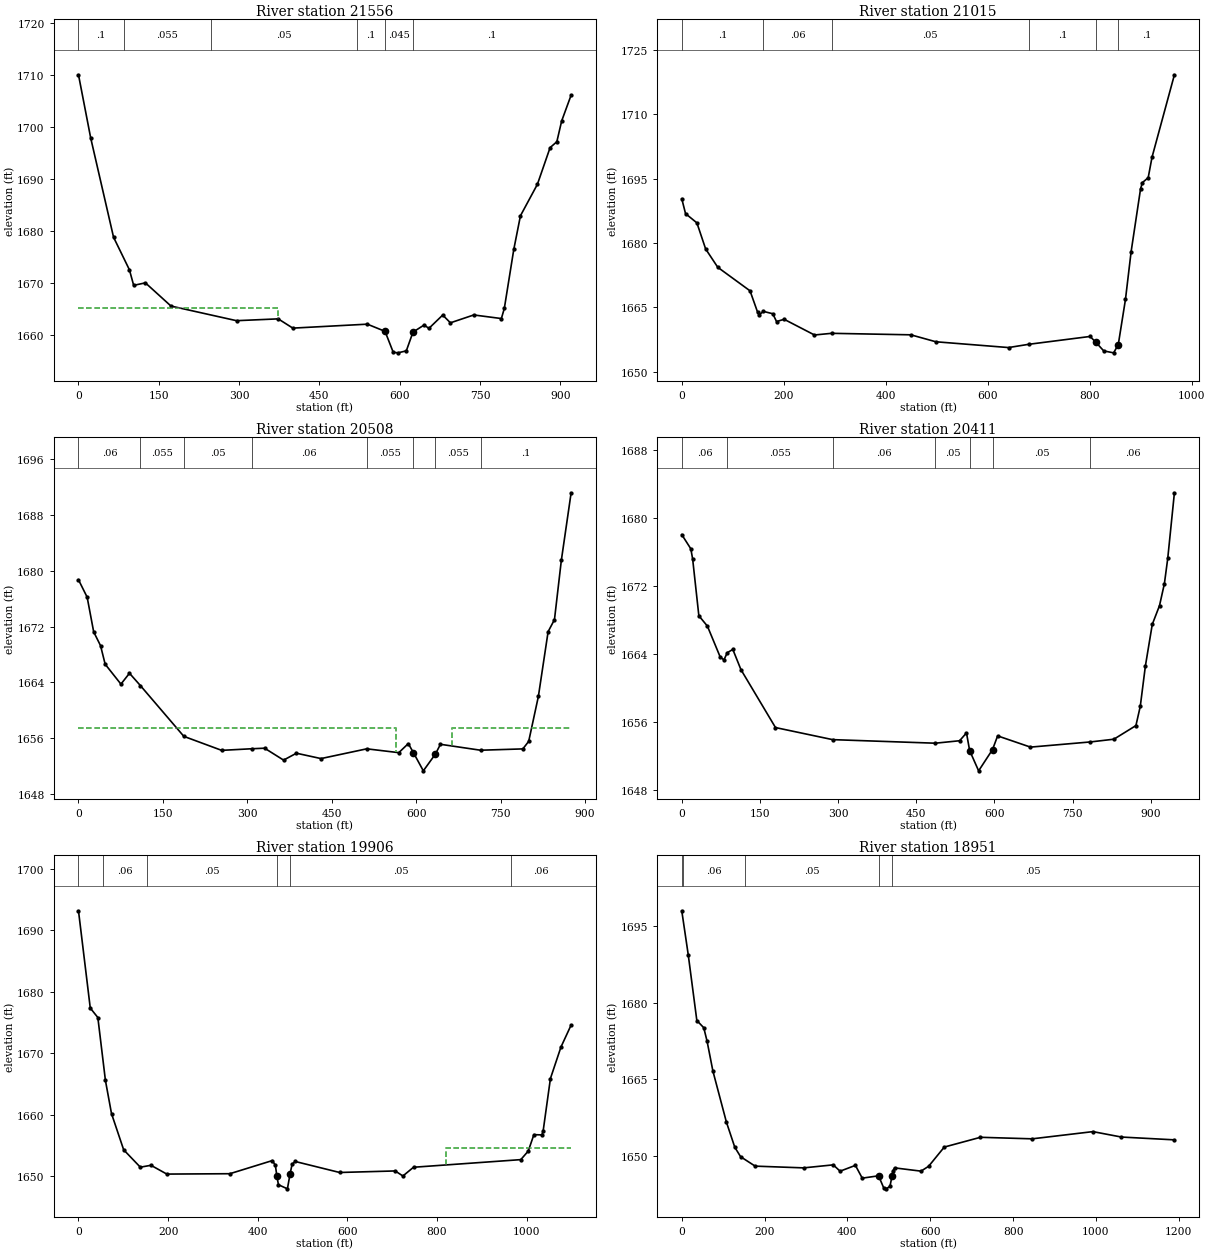
Type RM Length L Ch R = 1 ,21556   ,527.6,540.6,539.2
XS GIS Cut Line= 6
2072376.23945084302606.7927562152072277.28131545 302416.68847762
2072199.15614361302283.876079217 2072122.3334626302160.178163871
2071979.10409027302003.928148299 2071844.9895291301863.303101465
#Sta/Elev= 30
       0 1710.04    22.8  1697.9    65.5 1678.82    95.1 1672.57   103.1 1669.57
     125 1670.05   172.8 1665.59   295.2 1662.78   373.1 1663.13   400.4 1661.35
   539.6 1662.11  572.711660.729     588  1656.7   596.8  1656.6   612.4 1656.98
  624.891660.584   645.7 1661.95   654.6  1661.3   680.4 1663.86   694.8 1662.37
   738.4 1663.88     790 1663.19   795.5 1665.14   813.2 1676.49   825.6 1682.94
   857.3 1688.99     881 1696.04   893.6 1697.17   902.6 1701.16   920.3 1706.13
#Mann= 6 ,-1 , 0
       0      .1       0   84.71    .055       0  247.06     .05       0
  519.53      .1       0  572.71    .045       0  624.89      .1       0
#XS Ineff= 2 , 0
          372.95  1665.3
Permanent Ineff=
       F       F
Bank Sta=572.71,624.89
XS Rating Curve= 0 ,0
Exp/Cntr=0.3,0.1

Type RM Length L Ch R = 1 ,21015   ,497.2,507.3,509.3
XS GIS Cut Line= 2
2072798.33145443302437.0877150452072343.47048754  301584.6573333
#Sta/Elev= 30
       0 1690.35     7.4 1686.88    29.7 1684.72    46.8 1678.65    70.6 1674.37
   133.9 1668.88   148.7 1663.91   152.4 1663.31   159.9  1664.1   178.5 1663.54
   185.9 1661.72   200.8 1662.25   260.3 1658.59   293.8 1658.98   449.3 1658.63
   498.3 1657.01   640.9 1655.66   680.5 1656.42   800.9 1658.25  812.261656.874
   827.6 1654.88     847 1654.43   856.11656.343   870.2 1666.87   881.3 1678.01
   899.9 1692.72   903.6 1694.12   914.8 1695.26   922.3 1700.03   966.2 1719.24
#Mann= 6 ,-1 , 0
       0      .1       0   159.9     .06       0   293.8     .05       0
   680.5      .1       0  812.26    .045       0   856.1      .1       0
Bank Sta=812.26,856.1
XS Rating Curve= 0 ,0
Exp/Cntr=0.5,0.3

Type RM Length L Ch R = 1 ,20508   ,95.4,97.3,96.8
XS GIS Cut Line= 6
2073119.51224253302162.782161295 2073044.8595047301964.865562379
2073003.19259328301864.1712099612072914.65110371301678.407145798
2072874.72040927301499.5879496342072824.37339711 301341.60171704
#Sta/Elev= 30
       0 1678.71    15.4 1676.21      27 1671.23    39.2 1669.25    47.4 1666.59
    75.4 1663.73    90.6 1665.29   110.1 1663.51   187.2 1656.23   254.4 1654.22
   307.6 1654.45   330.7 1654.53   364.4 1652.82   387.2 1653.81   430.9 1653.04
   512.2 1654.44   569.1 1653.89     586 1655.19     5951653.906   612.7 1651.28
  634.261653.699   643.1 1655.09   714.3 1654.24   789.5 1654.43   799.9 1655.51
   817.1 1661.96   834.4 1671.26   845.7 1672.99   857.9  1681.5   875.3  1691.2
#Mann= 8 ,-1 , 0
       0     .06       0   110.1    .055       0   187.2     .05       0
   307.6     .06       0   512.2    .055       0     595    .045       0
  634.26    .055       0   714.3      .1       0
#XS Ineff= 2 , 0
             565  1657.5  664.26          1657.5
Permanent Ineff=
       F       F
Bank Sta=595,634.26
XS Rating Curve= 0 ,0
Exp/Cntr=0.5,0.3

Type RM Length L Ch R = 1 ,20411   ,504.8,504.3,502
XS GIS Cut Line= 4
2073171.59547168302135.0043297112073015.34545609301744.379454792
 2072980.6230846301529.1016701312072952.84558111301223.546178877
#Sta/Elev= 30
       0 1678.08    17.4 1676.41    20.9 1675.21    32.8 1668.54    49.2 1667.32
    73.9 1663.67      81 1663.35    87.3 1664.19      98 1664.58   113.6  1662.2
   179.9 1655.39   289.5 1653.97   486.7 1653.55   533.3 1653.84   546.5 1654.76
  552.561652.685   569.8  1650.3  596.471652.801   606.3 1654.41   669.3 1653.09
   784.5  1653.7   829.4 1654.02   871.7 1655.62   880.1 1657.89   889.9 1662.63
   903.1 1667.52     917 1669.73   926.4 1672.32   932.8 1675.28   945.6    1683
#Mann= 7 ,-1 , 0
       0     .06       0    87.3    .055       0   289.5     .06       0
   486.7     .05       0  552.56    .045       0  596.47     .05       0
   784.5     .06       0
Bank Sta=552.56,596.47
XS Rating Curve= 0 ,0
Exp/Cntr=0.5,0.3

Type RM Length L Ch R = 1 ,19906   ,961.1,955.4,941.8
XS GIS Cut Line= 3
 2073589.1238361301940.8951378762073393.81779626301178.407161549
2073329.58170426300872.851670295
#Sta/Elev= 30
       0  1693.2    26.3 1677.38    43.2 1675.84    60.1 1665.61    73.7 1660.21
   100.8 1654.33     138  1651.5   161.7 1651.81   197.1 1650.38   337.8 1650.44
   432.7 1652.58   439.4 1651.78  442.751650.005   446.2 1648.65   466.2 1647.98
  472.261650.464   476.7 1651.98   483.5 1652.43   582.7 1650.64   706.7 1650.89
   723.9 1650.07   747.6 1651.49     987 1652.73  1003.6 1654.12  1016.2 1656.79
  1034.1 1656.75  1036.9 1657.41  1053.1 1665.92  1076.6 1671.04  1099.3 1674.62
#Mann= 6 ,-1 , 0
       0      .1       0   55.23     .06       0   153.2     .05       0
  442.75    .045       0  472.26     .05       0  966.06     .06       0
#XS Ineff= 2 , 0
                          821.05          1654.7
Permanent Ineff=
       F       F
Bank Sta=442.75,472.26
XS Rating Curve= 0 ,0
Exp/Cntr=0.3,0.1

Type RM Length L Ch R = 1 ,18951   ,722.3,731.8,724.7
XS GIS Cut Line= 2
2074525.76205468301445.7685034572073577.84531537300727.018300548
#Sta/Elev= 30
       0 1697.94    15.6 1689.36    36.4 1676.48    53.1 1675.07    61.1 1672.44
    75.2 1666.59   107.7 1656.64     128  1651.7   142.1 1649.84   177.2    1648
   294.3 1647.66   365.8 1648.25   382.3 1647.01   419.3 1648.15   435.8 1645.65
  475.181646.108   487.8 1643.72   493.4 1643.56   502.7 1644.04  507.961646.147
   509.7 1647.07     514 1647.66   577.7 1647.02   596.1 1647.97   633.9 1651.73
   721.3 1653.64   846.2 1653.34   992.8 1654.75  1061.6 1653.69  1189.6 1653.14
#Mann= 5 ,-1 , 0
       0      .1       0    2.13     .06       0  151.84     .05       0
  475.18    .045       0  507.96     .05       0
Bank Sta=475.18,507.96
XS Rating Curve= 0 ,0
Exp/Cntr=0.3,0.1