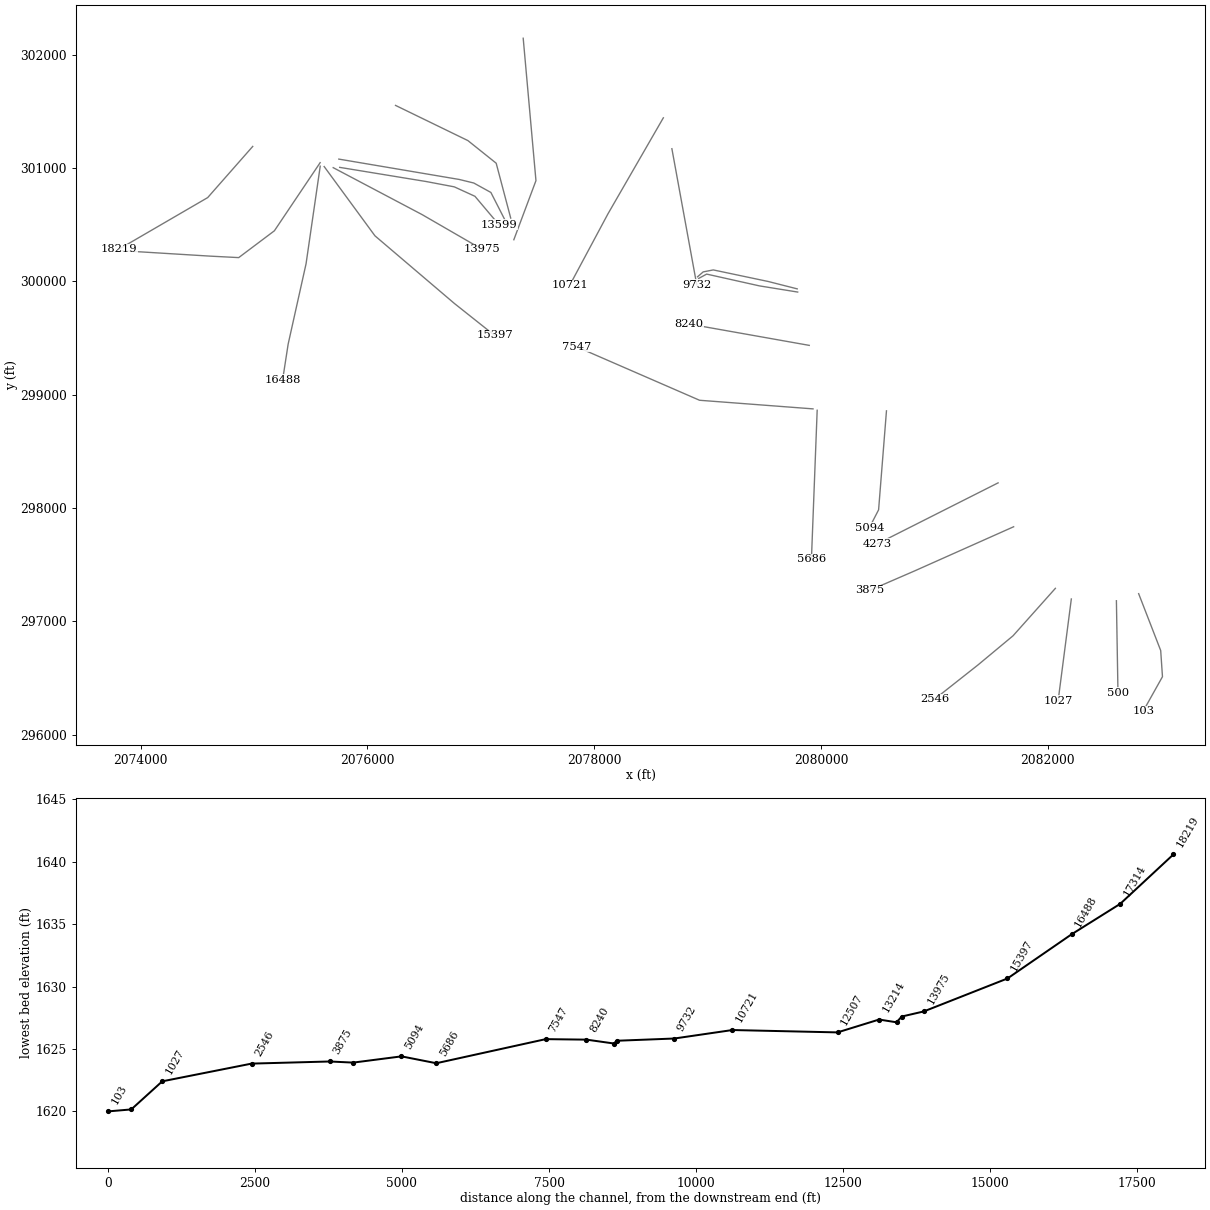
HEC-RAS study KTCHNCK.prj: KTCHNCK

--- KTCHNCK.g01 (geometry) --- (continued)

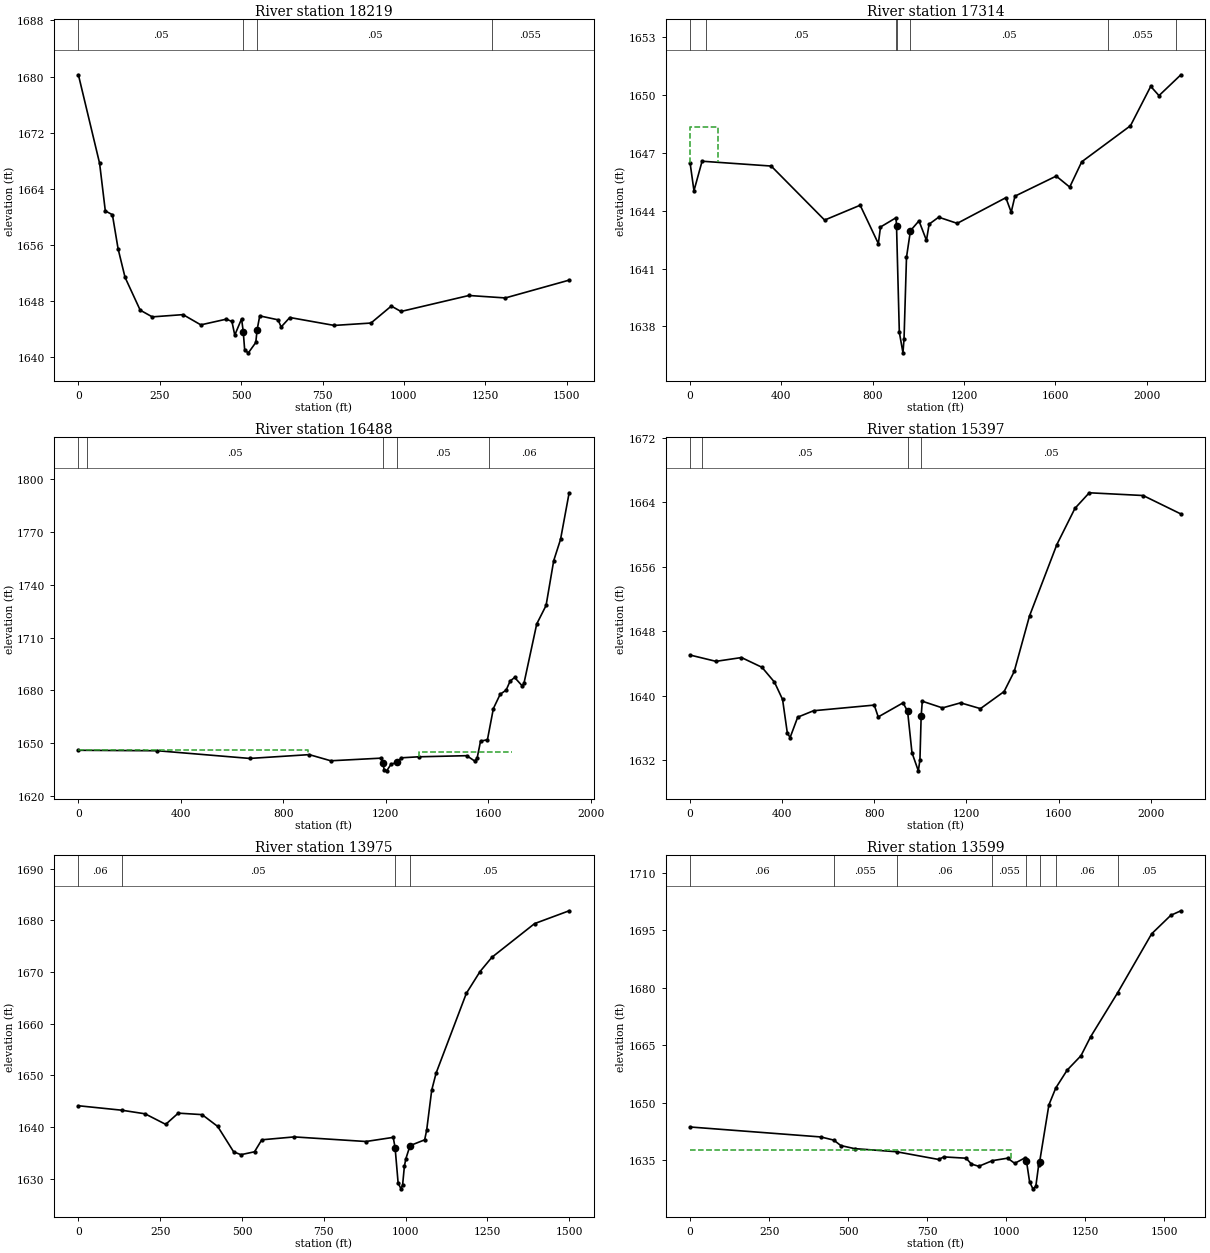
Type RM Length L Ch R = 1 ,18219   ,894.2,904.8,878.8
XS GIS Cut Line= 3
2074988.00161576301190.1259701252074590.86625519300738.737109125
2073807.44623411300283.008033708
#Sta/Elev= 30
       0 1680.25    65.2 1667.61    82.7 1660.83   104.5 1660.29     122 1655.42
   143.3 1651.36   189.8 1646.68   226.9 1645.72   321.5 1646.04   376.1 1644.58
   454.1 1645.39   471.6 1645.07   480.4 1643.12   501.3 1645.44  506.461643.608
   510.9 1640.95   522.2 1640.59     545 1642.07  548.941643.849   557.1 1645.86
   613.3  1645.3   622.9 1644.28   649.4 1645.63   785.9  1644.5   898.8 1644.84
   961.2 1647.26     991 1646.49  1199.7 1648.77  1311.6 1648.42  1507.6 1650.96
#Mann= 4 ,-1 , 0
       0     .05       0  506.46    .045       0  548.94     .05       0
    1270    .055       0
Bank Sta=506.46,548.94
XS Rating Curve= 0 ,0
Exp/Cntr=0.3,0.1

Type RM Length L Ch R = 1 ,17314   ,816.9,826.5,833.4
XS GIS Cut Line= 5
2075582.61984912301046.8969258822075178.97400287 300445.76820688
2074864.30370045300209.2230762992074612.56765535300222.244047627
 2073833.4878487 300269.98706238
#Sta/Elev= 30
       0 1646.46    16.8 1645.03    52.4 1646.56   355.2 1646.31   589.3 1643.51
   745.1 1644.28   824.8 1642.29   834.1 1643.15   902.1 1643.63   904.4 1643.22
   916.7  1637.7   932.6 1636.63   937.3 1637.35   948.1 1641.58   965.4 1642.96
  1002.8 1643.47  1035.5 1642.46  1047.4  1643.3  1089.1 1643.66  1170.4 1643.34
  1383.4 1644.67  1406.9 1643.92  1423.4 1644.75  1604.2 1645.79  1663.3 1645.22
  1715.9 1646.53  1929.6  1648.4  2018.3 1650.44  2054.5 1649.96  2150.4 1651.04
#Mann= 7 ,-1 , 0
       0     .06       0   70.46     .05       0   902.1    .045       0
   904.4    .045       0   965.4     .05       0 1830.62    .055       0
  2131.2     .05       0
#XS Ineff= 2 , 0
          120.88 1648.34
Permanent Ineff=
       F       F
Bank Sta=904.4,965.4
XS Rating Curve= 0 ,0
Exp/Cntr=0.3,0.1

Type RM Length L Ch R = 1 ,16488   ,1065.8,1090.6,1108.5
XS GIS Cut Line= 4
2075583.34327286301015.9360297922075458.34319478300154.825219214
2075300.43627136299446.1736594752075251.53542873299129.599638837
#Sta/Elev= 30
       0 1645.88   308.8 1645.62   669.1 1641.25   901.6 1643.41   985.6 1639.91
    1182 1641.41 1189.09  1638.5    1194 1634.87    1204 1634.19  1220.9 1637.94
  1244.4 1639.04  1261.3  1641.6  1328.5 1642.17  1516.7 1642.81    1547 1639.82
    1557 1641.27  1570.5 1651.08  1597.4 1651.89  1620.6 1669.63  1647.2 1677.75
  1670.4  1680.1  1686.2  1685.3  1703.6 1687.29  1733.5 1682.47  1740.1 1683.99
  1789.9 1717.73  1826.4 1728.25  1856.3 1753.79  1882.9 1765.82  1916.5 1792.35
#Mann= 5 ,-1 , 0
       0     .06       0   33.37     .05       0 1189.09    .045       0
  1244.4     .05       0 1602.79     .06       0
#XS Ineff= 2 ,-1
       0   895.7 1645.99 1331.41  1692.3 1644.92
Permanent Ineff=
       F       F
Bank Sta=1189.09,1244.4
XS Rating Curve= 0 ,0
Exp/Cntr=0.3,0.1

Type RM Length L Ch R = 1 ,15397   ,1400,1422.5,1410
XS GIS Cut Line= 4
2075618.06531626301012.4639238722076065.98207137300401.352941379
2076766.17432266299804.9513317322077121.21243878299522.863634216
#Sta/Elev= 30
       0 1645.02   112.2 1644.24     223 1644.71     312  1643.5   366.2 1641.66
   401.4 1639.51   422.1 1635.34   434.1 1634.78   467.1 1637.31     536 1638.11
   799.5 1638.81   816.7 1637.34   924.5 1639.09  944.241638.052   963.3  1632.9
   990.9 1630.65   997.9 1632.01 1003.151637.434  1008.1 1639.29  1095.6 1638.46
  1174.4 1639.09  1260.6 1638.37  1363.3 1640.49  1407.2 1642.98  1473.6 1649.87
  1592.5 1658.74    1671 1663.23  1733.1 1665.16    1967 1664.82  2130.9 1662.53
#Mann= 4 ,-1 , 0
       0     .06       0      50     .05       0  944.24    .045       0
 1003.15     .05       0
Bank Sta=944.24,1003.15
XS Rating Curve= 0 ,0
Exp/Cntr=0.3,0.1

Type RM Length L Ch R = 1 ,13975   ,370.8,375.4,373.7
XS GIS Cut Line= 3
2075697.75282094301002.7418304682076481.60689628300588.679338381
2077012.85714611300281.387630135
#Sta/Elev= 30
       0 1644.09   132.1 1643.23   203.8 1642.53   266.9 1640.49   305.3 1642.66
   378.2 1642.37   425.8 1640.09   474.7 1635.16     497 1634.62   538.4 1635.18
   560.6  1637.5   659.8 1638.06   879.1 1637.17   962.4 1637.97  968.111635.987
   977.5 1629.07   986.4 1628.01   991.2 1628.81   996.5 1632.36  1000.8 1633.78
 1013.811636.374  1058.5 1637.49  1064.7 1639.38  1080.1 1647.11  1093.5 1650.41
    1186 1665.85  1227.7 1670.05  1263.9 1672.81  1394.6 1679.34  1500.2 1681.82
#Mann= 4 ,-1 , 0
       0     .06       0   132.1     .05       0  968.11    .045       0
 1013.81     .05       0
Bank Sta=968.11,1013.81
XS Rating Curve= 0 ,0
Exp/Cntr=0.5,0.3

Type RM Length L Ch R = 1 ,13599   ,81.3,88.3,95.5
XS GIS Cut Line= 5
 2075755.0447011301005.3458278782076518.06548476300880.345749795
2076765.46131545300833.470843539 2076947.7529456 300750.13767688
2077158.69051585300500.137520716
#Sta/Elev= 30
       0 1643.73   413.8 1641.13   454.4 1640.31   476.6 1638.89   520.1 1638.09
   653.2 1637.27   786.2 1635.26   802.4 1635.93   873.1 1635.59   889.7 1634.07
   913.1 1633.48   956.5 1634.96  1004.5  1635.6  1026.8 1634.25  1058.9 1635.66
 1063.781634.991    1074 1629.37  1084.5  1627.6  1093.6 1628.26  1102.5 1633.74
 1105.811634.708    1135  1649.5  1156.7  1653.9  1192.7 1658.56  1236.5 1662.32
  1266.7 1667.22  1352.3 1678.72    1460 1694.11  1520.5 1698.93  1552.5 1700.12
#Mann= 8 ,-1 , 0
       0     .06       0   454.4    .055       0   653.2     .06       0
   956.5    .055       0 1063.78    .045       0 1105.81    .055       0
  1156.7     .06       0  1352.3     .05       0
#XS Ineff= 2 , 0
         1013.78  1637.8 1155.81          1637.8
Permanent Ineff=
       F       F
Bank Sta=1063.78,1105.81
XS Rating Curve= 0 ,0
Exp/Cntr=0.5,0.3

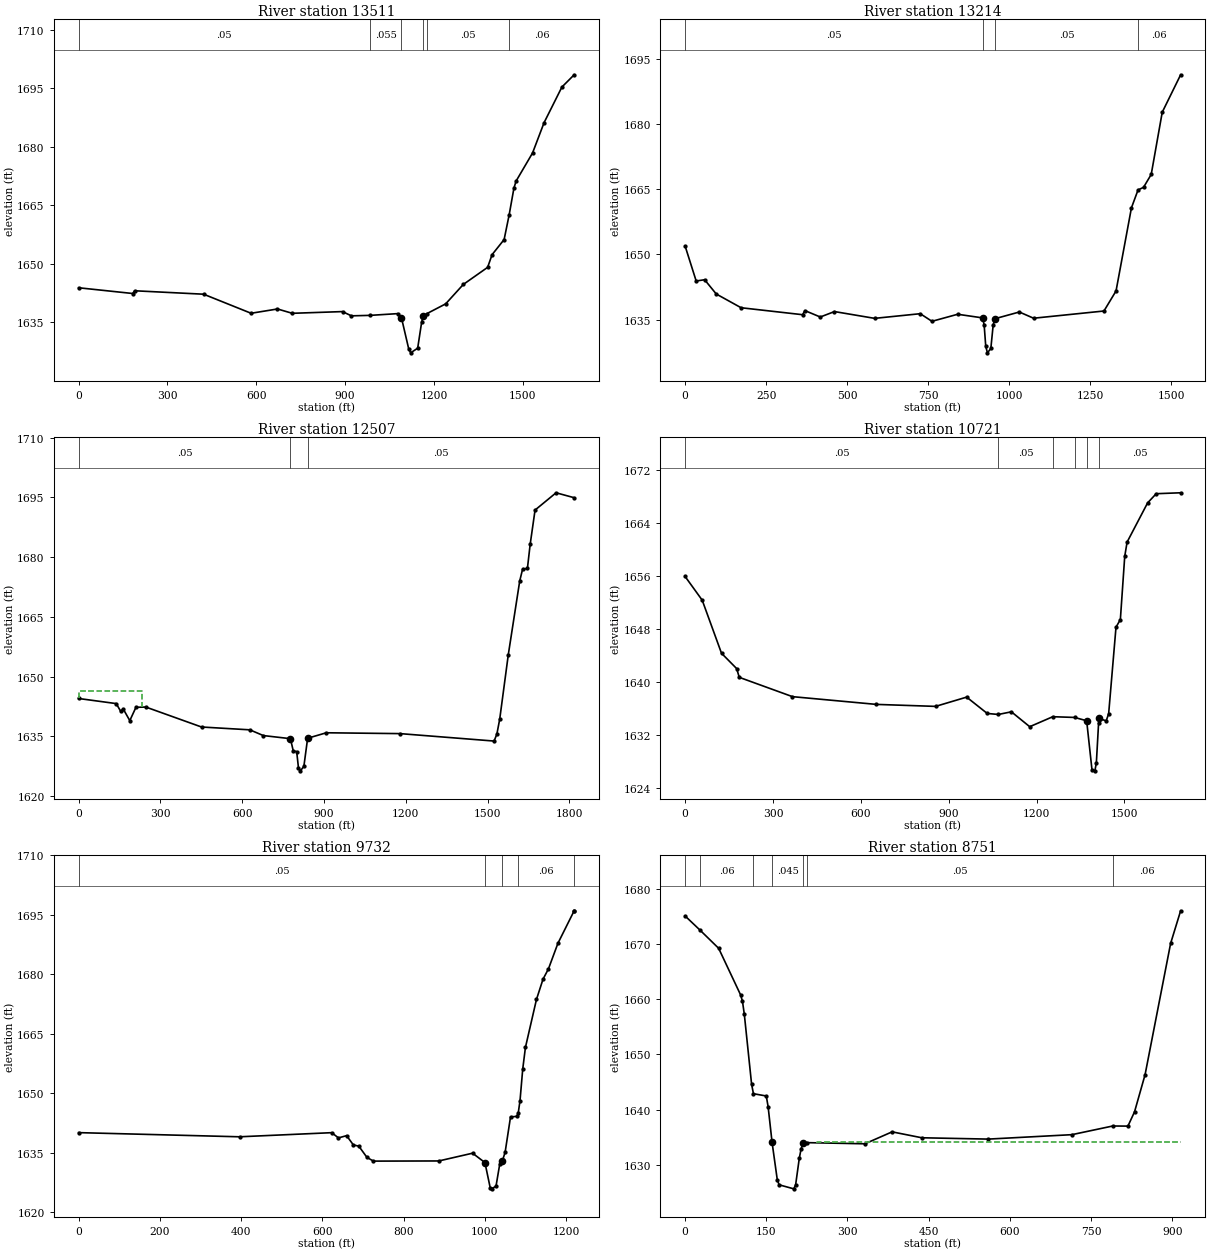
Type RM Length L Ch R = 1 ,13511   ,317.9,296.8,282.2
XS GIS Cut Line= 5
2075747.23205268 301078.262676792076809.73189619300898.575044051
2076937.33629978300867.3251065462077088.37799245300783.991611794
2077221.19039086300523.575137883
#Sta/Elev= 30
       0 1643.83   182.5 1642.36   189.2 1643.06   422.1 1642.18   582.5 1637.29
   671.7 1638.39   721.6 1637.28   891.3 1637.72   921.2 1636.63   984.4 1636.75
  1078.3  1637.2  1090.41636.151  1114.8  1628.2  1121.5 1627.14  1145.2 1628.33
  1158.7 1635.05  1164.11636.462  1175.6 1637.17  1239.7  1639.7  1299.3 1644.68
  1381.5 1649.07  1396.4 1652.31  1437.2  1656.2  1454.2 1662.53  1470.3 1669.39
  1477.7 1671.21  1533.2  1678.4  1572.2 1686.19  1632.4 1695.32  1673.8 1698.46
#Mann= 6 ,-1 , 0
       0     .05       0   984.4    .055       0  1090.4    .045       0
  1164.1    .055       0  1175.6     .05       0  1454.2     .06       0
Bank Sta=1090.4,1164.1
XS Rating Curve= 0 ,0
Exp/Cntr=0.5,0.3

Type RM Length L Ch R = 1 ,13214   ,712,706.8,676.4
XS GIS Cut Line= 4
2076247.48531726301551.9677661212076885.50602287 301241.63800621
2077135.07212478301041.9851902872077263.11025453300558.044229046
#Sta/Elev= 30
       0 1651.93    34.2 1643.88    60.3 1644.17    96.2 1640.89   172.9 1637.73
   362.6 1636.13   369.9 1637.07   417.3  1635.6   461.1 1636.85   585.1 1635.29
   725.9 1636.36   762.1 1634.61   841.4 1636.23  918.211635.399   923.1 1633.82
   928.1 1628.86   933.3 1627.36   943.8 1628.36   951.1 1633.83  957.341635.226
  1031.7 1636.75  1075.8 1635.32    1293 1636.98  1330.3 1641.59  1377.8  1660.7
  1398.2 1664.82  1415.2 1665.42  1438.9 1668.39  1472.9 1682.69  1529.7  1691.3
#Mann= 4 ,-1 , 0
       0     .05       0  918.21    .045       0  957.34     .05       0
  1398.2     .06       0
Bank Sta=918.21,957.34
XS Rating Curve= 0 ,0
Exp/Cntr=0.3,0.1

Type RM Length L Ch R = 1 ,12507   ,1787.3,1786.1,1753.1
XS GIS Cut Line= 3
2077373.27369268302144.6290961752077485.78225557300888.283477246
2077290.76741323300366.993802527
#Sta/Elev= 30
       0  1644.5   137.9 1643.22   154.3 1641.28   164.2  1641.8   187.7 1638.94
   210.3 1642.29   246.6 1642.35   450.8 1637.34   628.1 1636.63   677.5 1635.19
   776.9 1634.41   787.3 1631.37   799.9 1631.15   806.5 1627.07   813.5 1626.33
   826.3 1627.45   840.11634.515   908.6 1635.89  1178.8 1635.68  1524.1 1633.81
  1534.3 1635.55  1544.8 1639.33  1576.3 1655.54  1618.2 1674.04  1628.4 1676.91
  1646.4 1677.19  1656.4 1683.18  1674.4 1691.83  1751.5 1696.17  1817.9 1694.93
#Mann= 3 ,-1 , 0
       0     .05       0   776.9    .045       0   840.1     .05       0
#XS Ineff= 2 , 0
          234.04 1646.49
Permanent Ineff=
       F       F
Bank Sta=776.9,840.1
XS Rating Curve= 0 ,0
Exp/Cntr(USF)=0,0
Exp/Cntr=0.3,0.1

Type RM Length L Ch R = 1 ,10721   ,971.6,989.3,1000.7
XS GIS Cut Line= 3
2078609.16470428301442.4569952362078119.81377222300593.637452815
2077783.94353044299965.596266955
#Sta/Elev= 30
       0 1655.89    58.4 1652.31   124.3 1644.29   176.1 1641.97   184.9 1640.65
   366.7 1637.73   653.4 1636.56   855.2 1636.26   961.3 1637.66  1031.7 1635.19
  1069.5 1635.04  1114.1 1635.44  1176.7 1633.19  1255.5  1634.7  1329.9 1634.59
  1371.1 1634.09  1389.4 1626.63  1399.3 1626.52  1404.3 1627.78  1411.8 1633.71
  1414.7 1634.43  1437.8 1634.07  1446.2 1635.15  1471.3 1648.23  1486.2 1649.38
  1501.1 1658.93  1509.2 1661.09  1579.2 1667.01  1608.6  1668.4    1692 1668.54
#Mann= 6 ,-1 , 0
       0     .05       0  1069.5     .05       0  1255.5     .06       0
  1329.9     .05       0  1371.1    .045       0  1414.7     .05       0
Bank Sta=1371.1,1414.7
XS Rating Curve= 0 ,0
Exp/Cntr=0.3,0.1

Type RM Length L Ch R = 1 ,9732    ,1021.8,980.9,910.3
XS GIS Cut Line= 2
2078684.55130929301170.0233200492078903.73525411299969.936481372
#Sta/Elev= 30
       0 1640.03   396.2 1638.98     623 1640.02   639.6  1638.7   659.7 1639.27
   676.3 1636.92   689.7 1636.62   709.7 1633.79   725.7 1632.84   886.7 1632.88
   969.8 1634.84 1000.221632.467  1013.2 1626.11  1016.5 1625.84  1027.5 1626.52
  1036.5 1631.99 1042.851632.802  1049.9 1635.06  1063.2    1644  1079.9 1644.14
  1082.2 1644.98  1086.6 1648.12  1093.2 1656.03  1099.9 1661.54  1127.1 1673.66
  1143.2 1678.77  1156.6 1681.38  1179.9 1687.83  1219.3 1695.92  1219.9 1696.04
#Mann= 5 ,-1 , 0
       0     .05       0 1000.22    .045       0 1042.85     .05       0
  1082.2     .06       0  1219.3      .1       0
Bank Sta=1000.22,1042.85
XS Rating Curve= 0 ,0
Exp/Cntr=0.5,0.3

Type RM Length L Ch R = 1 ,8751    ,42.3,43.7,47
XS GIS Cut Line= 5
 2079789.7849912299933.4962655452079533.70840362299998.600466043
2079049.76744235300100.5969812132078960.79189852300083.235795468
2078910.87861252300039.832995132
#Sta/Elev= 30
       0 1675.03    28.2 1672.41      62 1669.18   102.6 1660.74     106 1659.59
   109.4 1657.26   122.9 1644.56   126.3 1642.87     150 1642.46   153.4 1640.52
  160.72 1634.05   170.3 1627.32   173.7 1626.39   200.8 1625.66   204.2 1626.37
     211 1631.19   214.3 1632.87  218.551634.012   224.5 1634.02   332.2 1633.81
   382.5 1635.97   437.4  1634.9   560.2 1634.66   714.6 1635.46   790.2 1637.03
   818.2 1637.01   830.4 1639.59   849.9 1646.32   897.1 1670.07   915.6 1675.97
#Mann= 7 ,-1 , 0
       0      .1       0    28.2     .06       0   126.3      .1       0
  160.72    .045       0  218.55      .1       0   224.5     .05       0
   790.2     .06       0
#XS Ineff= 2 , 0
           135.7  1634.1   243.5          1634.1
Permanent Ineff=
       F       F
Bank Sta=160.72,218.55
XS Rating Curve= 0 ,0
Exp/Cntr=0.5,0.3

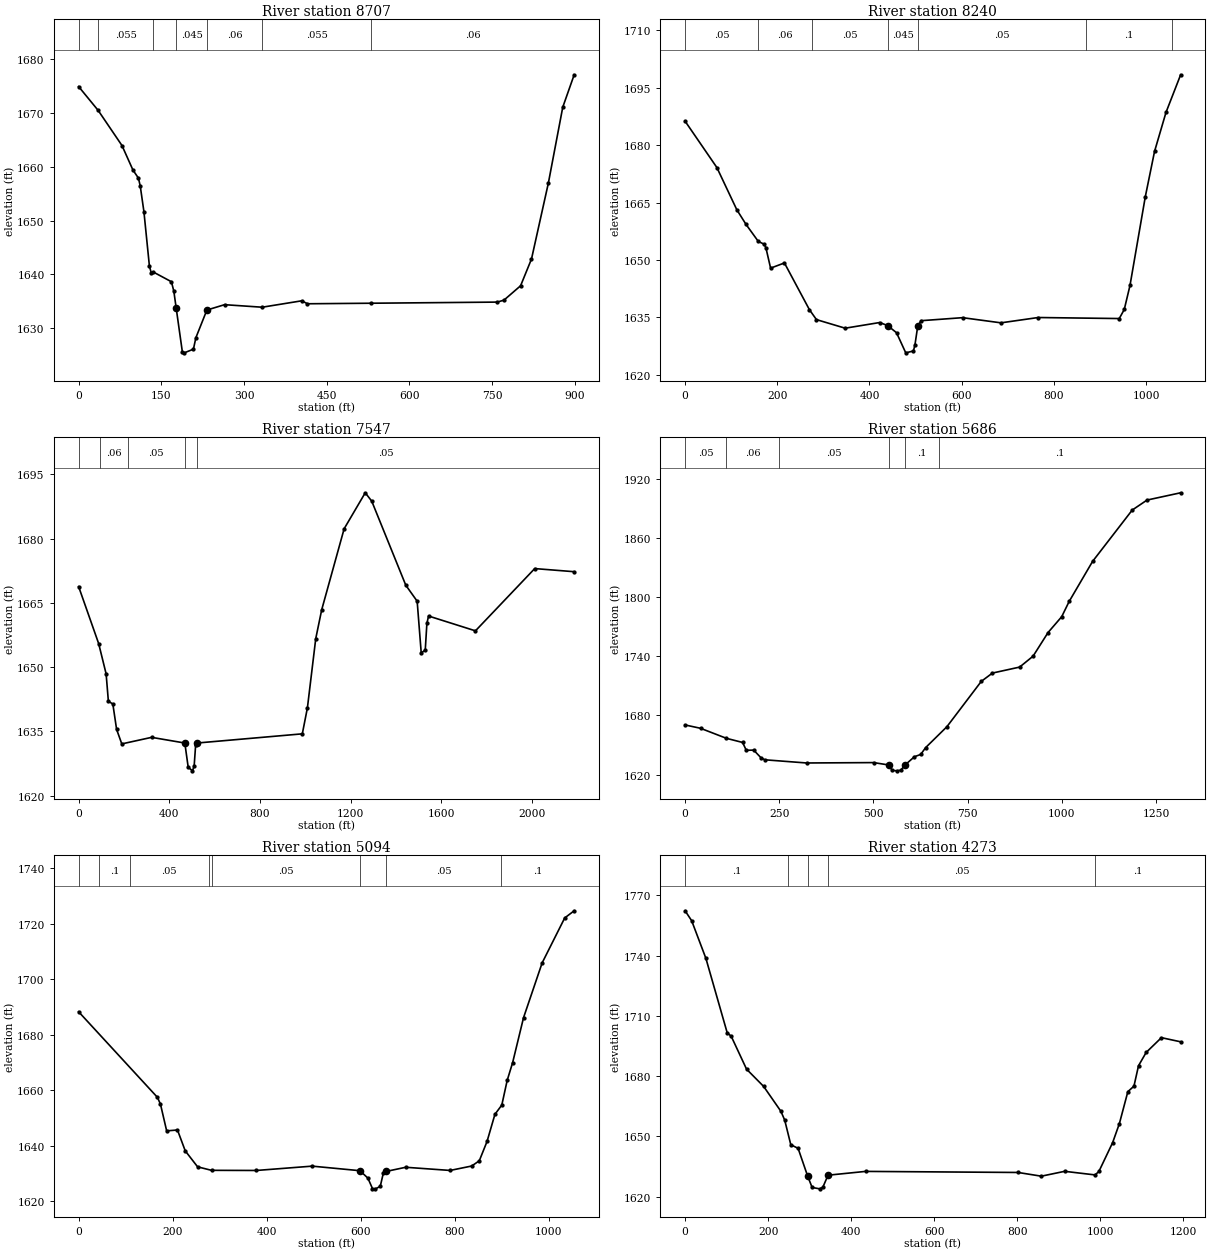
Type RM Length L Ch R = 1 ,8707    ,457.1,467.6,459.2
XS GIS Cut Line= 4
2079794.12520561299905.2843797062079457.75350302299959.537880123
2078991.17372751 300063.704666542078920.86120412300025.510189131
#Sta/Elev= 30
       0 1674.87    35.4 1670.45    78.6 1663.93    98.5 1659.38   108.5 1657.87
   111.8 1656.38   118.4 1651.67   128.4 1641.52   131.7  1640.3   135.1 1640.46
   168.3 1638.64   172.7 1636.87  176.911633.776   188.2 1625.57   191.6 1625.44
   208.2 1626.12   212.7 1628.26  232.611633.385   264.7 1634.38   332.9 1633.91
   404.7  1635.1   415.1 1634.55   530.9 1634.65   759.2 1634.86   771.4 1635.22
   801.6 1637.89   821.4 1642.86     852 1656.96   878.1 1671.04   898.8 1677.06
#Mann= 7 ,-1 , 0
       0     .05       0    35.4    .055       0   135.1     .06       0
  176.91    .045       0  232.61     .06       0   332.9    .055       0
   530.9     .06       0
Bank Sta=176.91,232.61
XS Rating Curve= 0 ,0
Exp/Cntr=0.5,0.3

Type RM Length L Ch R = 1 ,8240    ,678,693.1,688.4
XS GIS Cut Line= 2
 2079895.9045296299434.9283650522078837.39778835 299622.94931446
#Sta/Elev= 30
       0 1686.28    68.9 1674.18   112.2 1663.14   132.2 1659.31   158.8 1654.87
   172.1  1654.1   175.5 1653.11   185.5 1647.88   215.5 1649.24   269.8 1637.01
     285 1634.43   347.3 1632.19   422.1 1633.67  439.211632.893   458.7 1631.01
   478.7 1625.75   495.4 1626.24   498.7 1627.85  504.761632.766     512 1634.15
     602 1634.94   685.3 1633.59     766 1634.98   941.9 1634.71   952.8 1637.08
   965.2 1643.35   998.5 1666.58  1018.5 1678.39  1043.3 1688.57  1075.1 1698.41
#Mann= 7 ,-1 , 0
       0     .05       0  158.85     .06       0  275.09     .05       0
  439.21    .045       0  504.76     .05       0  868.85      .1       0
 1056.19     .05       0
Bank Sta=439.21,504.76
XS Rating Curve= 0 ,0
Exp/Cntr=0.3,0.1

Type RM Length L Ch R = 1 ,7547    ,1818,1860.4,1885.1
XS GIS Cut Line= 3
2079929.41168043298874.6853910392078928.69572522298950.644442326
2077844.57658463299422.409701289
#Sta/Elev= 30
       0 1668.81    88.4  1655.5   121.3 1648.43   131.2 1642.04   150.9  1641.4
   167.5 1635.47   190.4 1632.08     322 1633.61  468.411632.284   483.3 1626.63
   502.2 1625.79   509.6 1626.92   516.2 1631.86  520.821632.278   986.7 1634.43
  1009.2 1640.51    1046 1656.68  1072.2  1663.4  1171.2 1682.32  1264.3 1690.72
  1292.9 1688.77  1443.2 1669.13  1493.3  1665.4  1511.2 1653.33    1529 1653.98
  1536.2 1660.22  1543.6 1661.94  1750.4 1658.48  2011.9 1673.02  2185.9 1672.29
#Mann= 5 ,-1 , 0
       0     .05       0   93.98     .06       0  216.72     .05       0
  468.41    .045       0  520.82     .05       0
Bank Sta=468.41,520.82
XS Rating Curve= 0 ,0
Exp/Cntr=0.3,0.1

Type RM Length L Ch R = 1 ,5686    ,591.9,592,590.2
XS GIS Cut Line= 2
2079965.86994085298862.5325282072079915.17111918297548.131072959
#Sta/Elev= 30
       0 1670.39    40.9 1667.02   109.9 1656.81   152.6 1652.65   162.4 1644.71
   182.1 1644.88   201.8 1636.96   211.7 1635.06   322.6 1631.83   500.6 1632.22
  540.631629.805   549.8 1624.31     563 1623.86   572.8 1624.52  583.231629.613
   608.9  1638.2   625.4 1640.49   638.5 1647.41   694.9 1668.59   786.2 1714.57
   815.8 1723.01     888 1729.08   923.7 1740.15   963.5 1764.14   999.7 1780.18
  1019.4  1795.6  1081.7 1836.28  1186.9 1888.33  1226.2 1898.46  1315.4 1905.85
#Mann= 6 ,-1 , 0
       0     .05       0  107.86     .06       0  250.35     .05       0
  540.63    .045       0  583.23      .1       0  673.04      .1       0
Bank Sta=540.63,583.23
XS Rating Curve= 0 ,0
Exp/Cntr=0.3,0.1

Type RM Length L Ch R = 1 ,5094    ,840.6,821.5,790.4
XS GIS Cut Line= 3
2080576.98092335298857.3242052942080507.53650844297984.060531884
2080425.93923068297826.074299291
#Sta/Elev= 30
       0 1688.21   167.5 1657.39     174 1654.94   187.2  1645.3   210.2 1645.61
   226.7  1638.1     253 1632.34   282.6 1631.08   378.1 1631.03   496.6 1632.59
  598.181630.947   615.1 1628.28   624.9  1624.5   631.3 1624.41   641.4 1625.29
     648 1630.09  653.751630.676   695.5 1632.18     790 1631.04   835.8 1632.63
     852 1634.51   868.5 1641.48   885.3 1651.27   899.9 1654.59   911.3 1663.46
   922.9 1669.87   946.1 1686.07   985.7 1705.83  1033.7 1722.02  1053.8  1724.6
#Mann= 8 ,-1 , 0
       0     .05       0   43.67      .1       0  108.43     .05       0
  276.36     .06       0  284.51     .05       0  598.18    .045       0
  653.75     .05       0  897.65      .1       0
Bank Sta=598.18,653.75
XS Rating Curve= 0 ,0
Exp/Cntr=0.3,0.1

Type RM Length L Ch R = 1 ,4273    ,398.5,397.5,396.3
XS GIS Cut Line= 2
2081561.35592312298221.9078252172080495.38397369297683.713363543
#Sta/Elev= 30
       0 1762.34    15.8  1757.4    50.1 1738.66   101.3 1701.71   111.3 1699.79
   148.1 1683.49   189.3 1674.89   230.8 1662.53     240 1658.14   254.7 1645.88
   272.3 1644.07  295.25 1630.29   306.1 1624.59   324.5 1623.91   331.9 1624.69
  344.461630.701   434.8 1632.59   802.3 1632.06   858.4 1630.21   914.6 1632.63
   987.9 1630.84   997.1 1632.55  1030.2  1646.9  1046.5 1656.39  1066.9 1672.29
  1081.6 1675.03  1092.6  1685.2    1111 1691.81  1147.8 1699.17  1194.1 1697.11
#Mann= 5 ,-1 , 0
       0      .1       0  246.93     .06       0  295.25    .045       0
  344.46     .05       0   988.7      .1       0
Bank Sta=295.25,344.46
XS Rating Curve= 0 ,0
Exp/Cntr=0.3,0.1

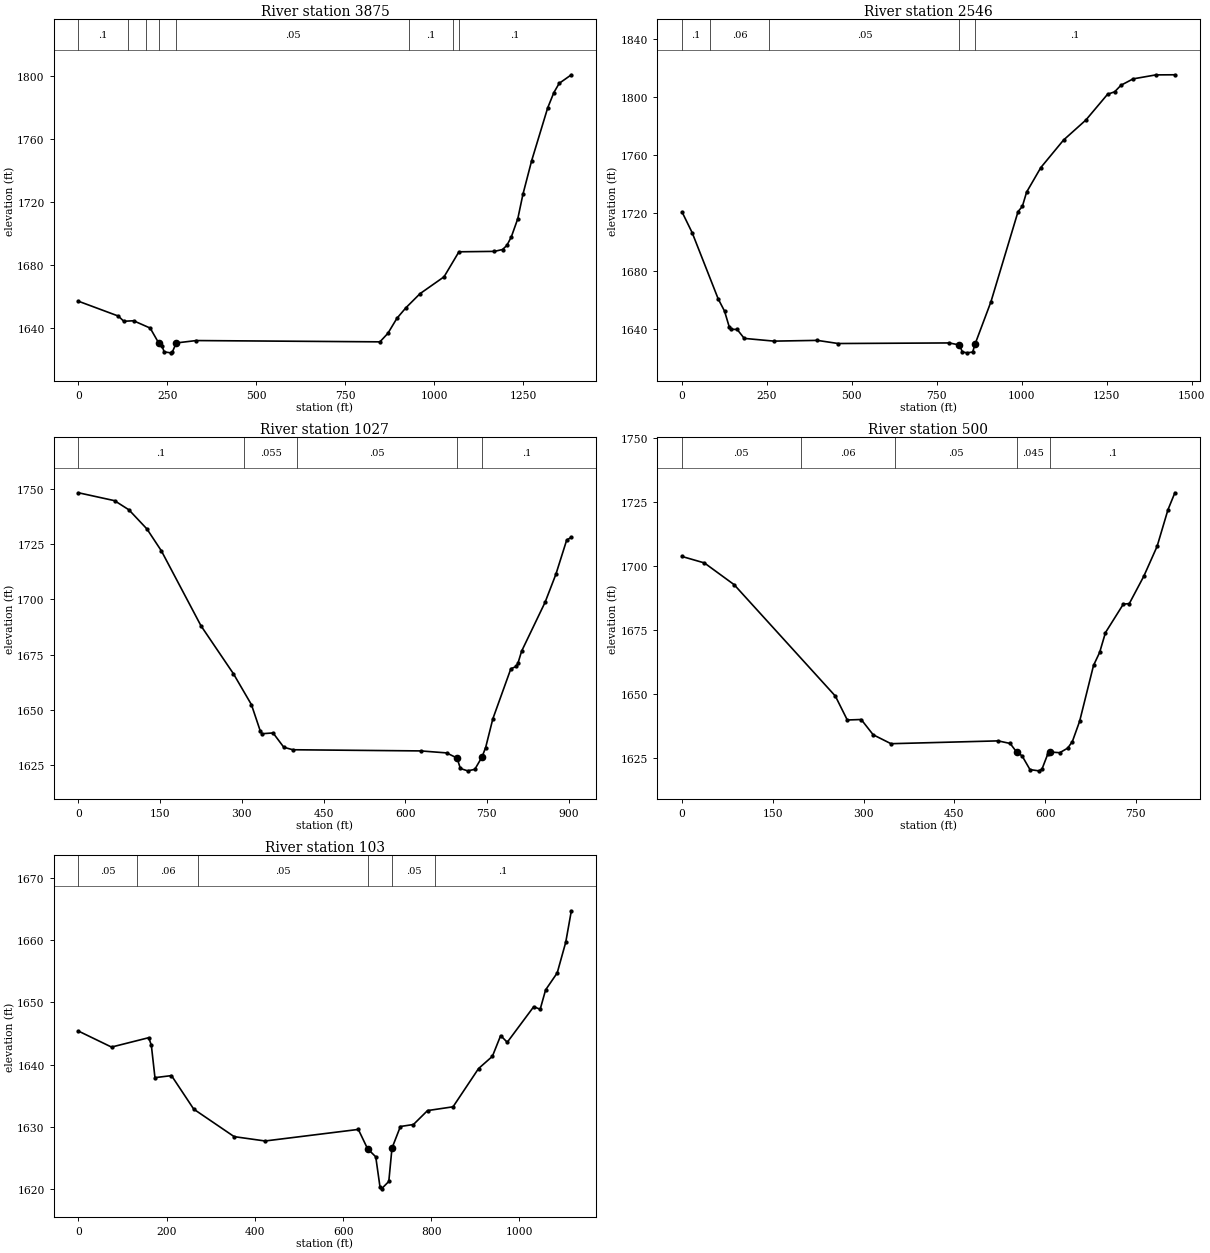
Type RM Length L Ch R = 1 ,3875    ,1321.1,1329,1330.1
XS GIS Cut Line= 3
2081698.50886402297834.7547281242080822.79557522297444.140183869
2080431.55421427297274.343938119
#Sta/Elev= 30
       0 1656.76   111.7 1647.38   127.4 1644.05   154.8 1644.37   201.5 1639.72
  225.711630.148   233.9 1628.66     241 1624.61     259    1624   264.1 1624.68
  274.771630.278   330.9  1631.8   847.3 1630.98   869.7 1636.39   895.1 1645.94
   920.2 1652.59     960 1661.57  1027.5 1672.27  1069.4 1688.16  1169.2 1688.43
    1192 1689.62  1204.1  1692.2  1216.6 1697.61  1234.9 1709.23  1249.2  1724.6
  1273.9 1746.09  1318.8 1779.51  1336.3  1789.3  1351.2 1795.13  1385.4 1800.57
#Mann= 8 ,-1 , 0
       0      .1       0  139.32     .06       0  189.51     .05       0
  225.71    .045       0  274.77     .05       0  930.42      .1       0
 1052.94     .05       0 1068.69      .1       0
Bank Sta=225.71,274.77
XS Rating Curve= 0 ,0
Exp/Cntr=0.3,0.1

Type RM Length L Ch R = 1 ,2546    ,1495.3,1519.5,1521.7
XS GIS Cut Line= 4
2082066.56423026297291.352271631 2081693.3005411296872.949237049
2081384.33308338296615.8723593322081001.33516077296313.564065857
#Sta/Elev= 30
       0 1720.88    29.9 1706.58   106.5 1660.98   125.1  1652.6   139.4  1641.4
   143.7 1640.03   162.3 1639.95   183.2 1633.78   270.7  1631.9   398.2 1632.41
   459.7 1630.25   786.6 1630.65  816.371629.226   825.2 1624.43   839.2 1623.83
   855.5 1624.39  862.251629.672   909.1  1658.9   989.1 1721.15  1001.7 1724.68
  1014.2 1734.52  1056.1 1751.45  1122.9 1770.38  1188.7 1784.18  1252.4 1801.89
  1273.4 1803.63    1292 1808.13  1327.7 1812.52  1394.6 1815.26  1450.6 1815.34
#Mann= 5 ,-1 , 0
       0      .1       0   81.74     .06       0  257.26     .05       0
  816.37    .045       0  862.25      .1       0
Bank Sta=816.37,862.25
XS Rating Curve= 0 ,0
Exp/Cntr=0.3,0.1

Type RM Length L Ch R = 1 ,1027    ,521.4,526.4,525.3
XS GIS Cut Line= 2
2082207.18927711297197.6021310392082090.86995593296300.032731965
#Sta/Elev= 30
       0 1748.18    66.2 1744.61    92.6 1740.47   125.7 1731.81   152.2 1721.91
   224.9 1688.03   284.5 1666.34   317.6 1652.34   334.1 1640.23   337.2  1639.2
   357.3 1639.55   377.1 1633.06   393.7 1631.95   628.6 1631.42     676 1630.52
   695.21628.197   701.3 1623.48   714.6 1622.41   727.8 1623.08  741.111628.726
   747.7 1632.95   760.9 1645.93     794 1668.59   803.9 1669.62   807.2 1671.24
   813.8 1676.56   856.8 1698.62   876.7 1711.33   896.5 1726.77   905.1 1728.08
#Mann= 5 ,-1 , 0
       0      .1       0  304.09    .055       0  401.64     .05       0
   695.2    .045       0  741.11      .1       0
Bank Sta=695.2,741.11
XS Rating Curve= 0 ,0
Exp/Cntr=0.3,0.1

Type RM Length L Ch R = 1 ,500     ,393.2,397.7,396.1
XS GIS Cut Line= 2
2082604.75869194297181.9771623022082618.64777178296367.740929872
#Sta/Elev= 30
       0 1703.72    36.9 1701.21    86.1 1692.74   253.4  1649.3   273.1 1639.98
   296.1 1640.17   315.9 1634.22   345.3 1630.74   522.4 1631.84   542.2 1630.83
  552.711627.557   561.9 1626.01     575 1620.64   589.4 1620.16   594.7 1620.76
   604.5 1626.78  608.311627.493   624.2 1627.23   637.3 1629.01     645 1631.57
     657 1639.47     680 1661.26   690.1 1666.33   699.7 1674.04   729.2 1685.13
   739.1 1685.36     763 1695.99     785 1707.64     803 1721.95   814.4 1728.55
#Mann= 5 ,-1 , 0
       0     .05       0  195.99     .06       0   352.1     .05       0
  552.71    .045       0  608.31      .1       0
Bank Sta=552.71,608.31
XS Rating Curve= 0 ,0
Exp/Cntr=0.3,0.1

Type RM Length L Ch R = 1 ,103     ,111.42,102.53,93.63
XS GIS Cut Line= 4
2082800.93940195297244.4770372962082995.38389495296742.740836039
2083011.00886369296511.8380826262082840.86976826 296208.01880838
#Sta/Elev= 30
       0 1645.38    74.9 1642.81   159.3 1644.32   165.2  1643.1   173.4 1637.89
   210.9 1638.22   261.4 1632.82     353  1628.4   423.2  1627.7   634.6 1629.56
  655.441626.468   674.1 1625.15   683.9 1620.22   687.2    1620   703.7 1621.19
  710.911626.544     730 1630.03   759.6 1630.35   791.5 1632.59   849.4  1633.2
   907.2 1639.35   938.6 1641.32   957.4 1644.66   972.3 1643.58  1032.4 1649.31
    1047 1648.89  1059.3 1652.01  1085.6 1654.74  1104.9 1659.66  1117.7 1664.74
#Mann= 6 ,-1 , 0
       0     .05       0  133.08     .06       0  272.09     .05       0
  655.44    .045       0  710.91     .05       0  809.02      .1       0
Bank Sta=655.44,710.91
XS Rating Curve= 0 ,0
Exp/Cntr=0.3,0.1
LCMann Table=0

Chan Stop Cuts=-1
Use User Specified Reach Order=0
Composite Channel Slope=5